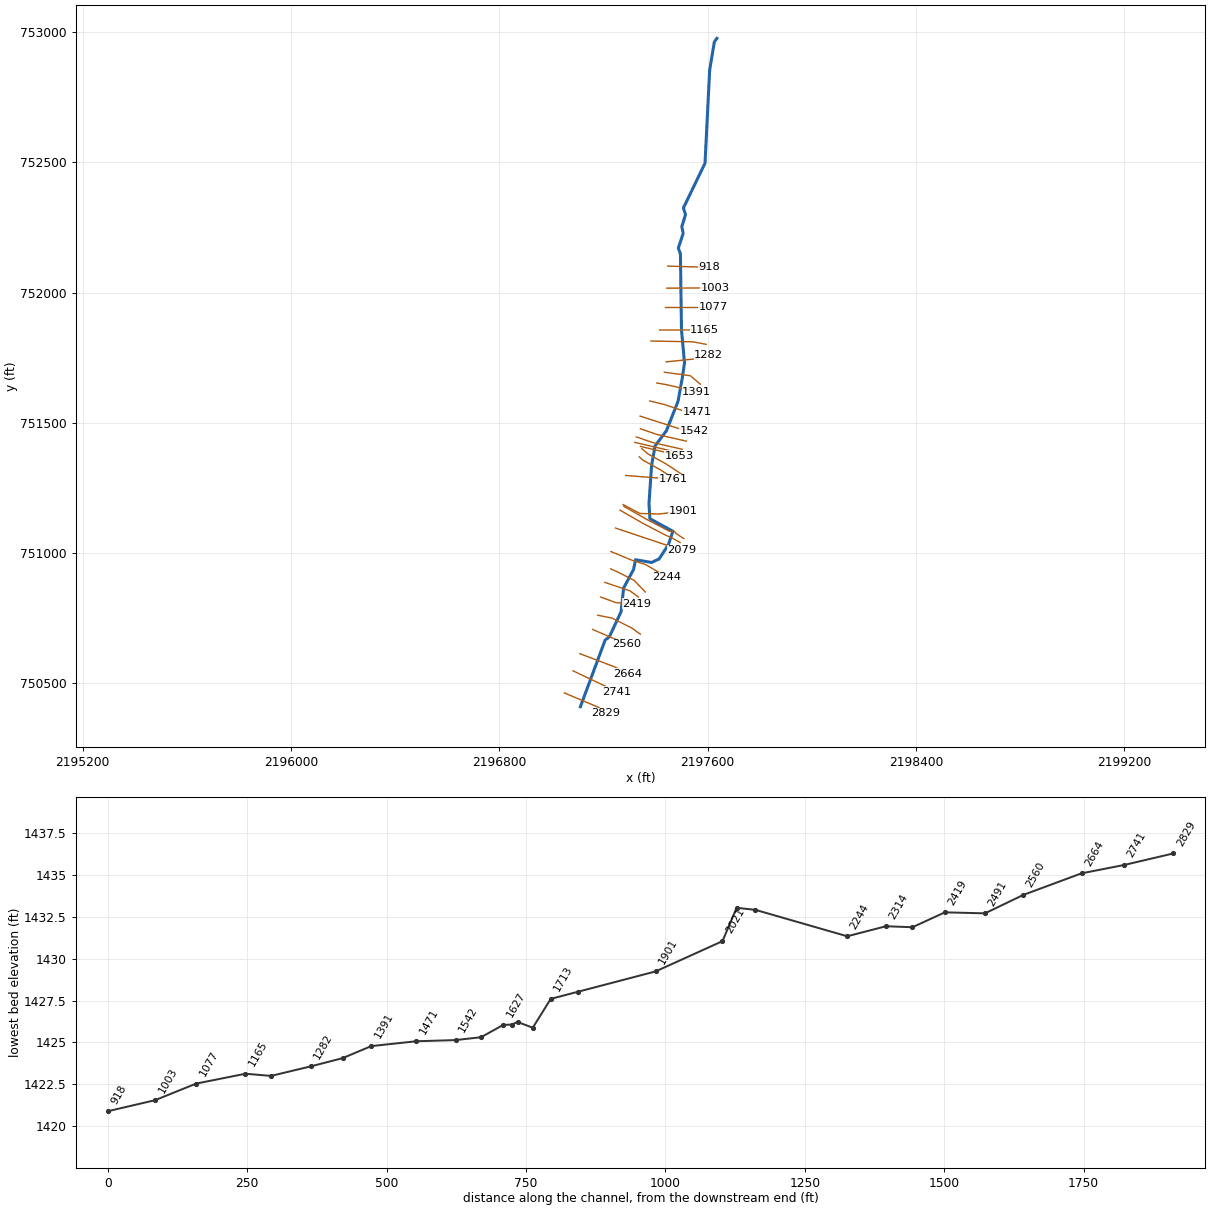
--- PECKSRNT4.prj (project) ---

Proj Title=PECKSRNT4
Current Plan=p01
Default Exp/Contr=0,0
English Units
Geom File=g01
Flow File=f01
Plan File=p01
BEGIN DESCRIPTION:
---------- MODELED AS PART OF WVEMD CTP PROGRAM, 2023----------
Stream Name: Pecks Run Tributary 4
Flood Zone:  AFH
Upshur County, WV
HEC-RAS Version: RAS 6.3
Vertical Datum: NAVD88
Projection: NAD 1983 StatePlane West Virginia S FIPS 4702 (US Feet)
Terrain: 1-meter LIDAR (FEMA Region III 3DEP collected 2016-2018)
Land Use: 2019 NLCD
Hydrologic Method:
WV SIR2010-5033 regression equations
Additional Model Notes:
None
END DESCRIPTION:
DSS Export Rating Curves= 0
DSS Export Rating Curve Sorted= 0
DSS Export Volume Flow Curves= 0
DXF OffsetX= 0
DXF OffsetY= 0
DXF ScaleX= 0
DXF ScaleY= 0

--- PECKSRNT4.p01 (plan) ---

Plan Title=Floodplain
Program Version=6.30
Short Identifier=Floodplain
Geom File=g01
Flow File=f01
Subcritical Flow
K Sum by GR= 0
Std Step Tol= 0.01
Critical Tol= 0.01
Num of Std Step Trials= 20
Max Error Tol= 0.3
Flow Tol Ratio= 0.001
Split Flow NTrial= 30
Split Flow Tol= 0.02
Split Flow Ratio= 0.02
Log Output Level= 0
Friction Slope Method= 1
Unsteady Friction Slope Method= 2
Unsteady Bridges Friction Slope Method= 1
Parabolic Critical Depth
Global Vel Dist= 0 , 0 , 0
Global Log Level= 0
CheckData=False
Encroach Param=-1 ,0,0, 0
Mapping Interval=1HOUR
Computation Time Step Use Courant=        0
Computation Time Step Use Time Series=    0
Computation Time Step Count To Double=0
Computation Time Step Max Doubling=0
Computation Time Step Max Halving=0
Computation Time Step Residence Courant=0
Run HTab= 0
Run UNet= 0
Run Sediment= 0
Run PostProcess= 0
Run WQNet= 0
Run RASMapper=-1
UNET Theta= 0
UNET Theta Warmup= 0
UNET ZTol= 0
UNET ZSATol= 0
UNET MxIter= 0
UNET Max Iter WO Improvement= 0
UNET MaxInSteps= 0
UNET DtIC= 0
UNET DtMin= 0
UNET MaxCRTS= 0
UNET WFStab= 0
UNET SFStab= 0
UNET WFX= 1
UNET SFX= 1
UNET Gravity=32.17405
UNET 1D Methodology=Finite Difference
UNET DSS MLevel= 1
UNET Pardiso=0
UNET DZMax Abort= 0
UNET Use Existing IB Tables= 0
UNET Froude Reduction=False
UNET Froude Limit= 0
UNET Froude Power= 0
UNET D1 Cores= 0
UNET WindReference=Eulerian
UNET WindDragFormulation=Hsu (1988)
UNET D2 Coriolis=0
UNET D2 Cores= 0
UNET D2 Theta= 1
UNET D2 Theta Warmup= 1
UNET D2 Z Tol= 0.01
UNET D2 Volume Tol= 0.01
UNET D2 Max Iterations= 20
UNET D2 Equation= 0
UNET D2 RampUpFraction=0.1
UNET D2 TimeSlices= 1
UNET D2 Turbulence Formulation=Non-Conservative (original)
UNET D2 Eddy Viscosity=0.3
UNET D2 Transverse Eddy Viscosity=0.1
UNET D2 Smagorinsky Mixing=0
UNET D2 BCVolumeCheck=0
UNET D2 Cores=0
UNET D2 SolverType=PARDISO (Direct)
UNET D2 Minimum Iterations= 3
UNET D2 Maximum Iterations= 30
UNET D2 Restart Number= 10
UNET D2 Relaxation Coeff=1.3
UNET D2 SOR Precondition Iterations= 10
UNET D2 ILUT Maximum Fill= 8
UNET D2 ILUT Tolerance=1E-08
UNET D2 Convergence Tolerance=0.00001
UNET D1D2 MaxIter= 0
UNET D1D2 ZTol=0.01
UNET D1D2 QTol=0.1
UNET D1D2 MinQTol=1
Write IC File= 0
Write IC File at Fixed DateTime=0
Write IC File at Sim End=0
Echo Input=False
Echo Parameters=False
Echo Output=False
Write Detailed= 0
HDF Write Warmup=0
HDF Write Time Slices=0
HDF Flush=0
HDF Compression= 1
HDF Chunk Size= 1
HDF Spatial Parts= 1
HDF Use Max Rows=0
HDF Fixed Rows= 1
Calibration Method= 0
Calibration Iterations= 20
Calibration Max Change=0.05
Calibration Tolerance=0.2
Calibration Maximum=1.5
Calibration Minimum=0.5
Calibration Optimization Method= 1
WQ AD Non Conservative
WQ ULTIMATE=-1
WQ Max Comp Step=1HOUR
WQ Output Interval=15MIN
WQ Output Selected Increments= 0
WQ Output face flow=0
WQ Output face velocity=0
WQ Output face area=0
WQ Output face dispersion=0
WQ Output cell volume=0
WQ Output cell surface area=0
WQ Output cell continuity=0
WQ Output cumulative cell continuity=0
WQ Output face conc=0
WQ Output face dconc_dx=0
WQ Output face courant=0
WQ Output face peclet=0
WQ Output face adv mass=0
WQ Output face disp mass=0
WQ Output cell mass=0
WQ Output cell source sink temp=0
WQ Output nsm pathways=0
WQ Output nsm derived pathways=0
WQ Create Restart=0
WQ Fixed Restart=0
WQ System Summary=0
WQ Write To DSS=0
Sorting and Armoring Iterations= 10
XS Update Threshold= 0.02
Bed Roughness Predictor= 0
Hydraulics Update Threshold= 0.02
Energy Slope Method= 1
Volume Change Method= 1
Sediment Retention Method= 0
Sediment TS Multiplier= 1
Warm Up Method= 0
XS Weighting Method= 0
Number of US Weighted Cross Sections= 1
Number of DS Weighted Cross Sections= 1
Upstream XS Weight=0
Main XS Weight=1
Downstream XS Weight=0
Number of DS XS's Weighted with US Boundary= 1
Upstream Boundary Weight= 1
Weight of XSs Associated with US Boundary= 0
Number of US XS's Weighted with DS Boundary= 1
Downstream Boundary Weight= 0.5
Weight of XSs Associated with DS Boundary= 0.5
Percentile Method= 0
Sediment Output Level= 3
Mass or Volume Output= 0
Output Increment Type= 1
Profile and TS Output Increment= 1
Transport Output Increment 1
XS Output Flag= 0
XS Output Increment= 10
Read HDF5 Sediment Hotstart= 0
Sediment Hotstart Type= 0
Write Gradation File= 0
Read Gradation Hotstart= 0
Write HDF5 File= 1
Write Binary Output= 1
Write DSS Sediment File= 0
DSS Sediment Output Type= 1
SV Curve= 0
Specific Gage Flag= 0
Subcell Erosion Methods= 0
Subcell Deposition Methods= 0
Advection Scheme= 1
Matrix Solver= 0
Implicit Weighting Factor= 1
Maximum Outer Loop Convergence Iterations= 5
Convergence Maximum Absolute= 0.001
Convergence RMSE= 0.0001
Grain Fractions Max Abs Error= 0.001
Max Subgrid Regions= 1
Max Subgrid Length Scale= 3.402823E+38
Initial Layer Thickness= 3.402823E+38
Min Layer Thickness= 3.402823E+38
Max Layer Thickness= 3.402823E+38
Number of Layers= 5

--- PECKSRNT4.f01 (steady flow) ---

Flow Title=Flows
Program Version=6.31
Number of Profiles= 1
Profile Names=01pct
River Rch & RM=PECKSRNT4,Main,2829
     134
River Rch & RM=PECKSRNT4,Main,1003
     150
Boundary for River Rch & Prof#=PECKSRNT4,Main            , 1
Up Type= 0
Dn Type= 3
Dn Slope=0.01239
DSS Import GetInterval= 0
DSS Import GetPeak= 0
DSS Import FillOption= 0

--- PECKSRNT4.g01 (geometry) ---

Geom Title=Geometry
Program Version=6.31

River Reach=PECKSRNT4       ,Main
Reach XY= 30
2197111.24299959750409.7486300682197206.41155076750666.143109527
2197222.42958039750678.0779005082197267.61800273750774.920679668
 2197277.2871625 750865.765808692197315.38564215750936.863480202
 2197322.9828122750974.3350119762197384.82714988750963.844161888
 2197413.6450689750977.5798058342197448.88915627751031.675381796
2197466.45193634 751083.69614943  2197378.120993751132.074353444
2197374.72214305751190.3724662882197384.71011717751336.589058926
2197397.91974433751411.0572536022197441.75688398751470.027476629
2197486.28677763751582.9594627832197502.93911474751674.126109238
2197511.14108184751730.2859728782197499.49874202751857.613369313
2197495.39586488752149.4864083292197487.34896608752171.404670261
 2197505.9869926752227.8133802982197500.81511645752253.672761085
2197515.13420396752300.204211011 2197506.8273052752325.150221033
2197589.90769051752497.3310416772197607.79003605752855.775137549
2197625.65652203752962.864055849     2197635.507      752976.742

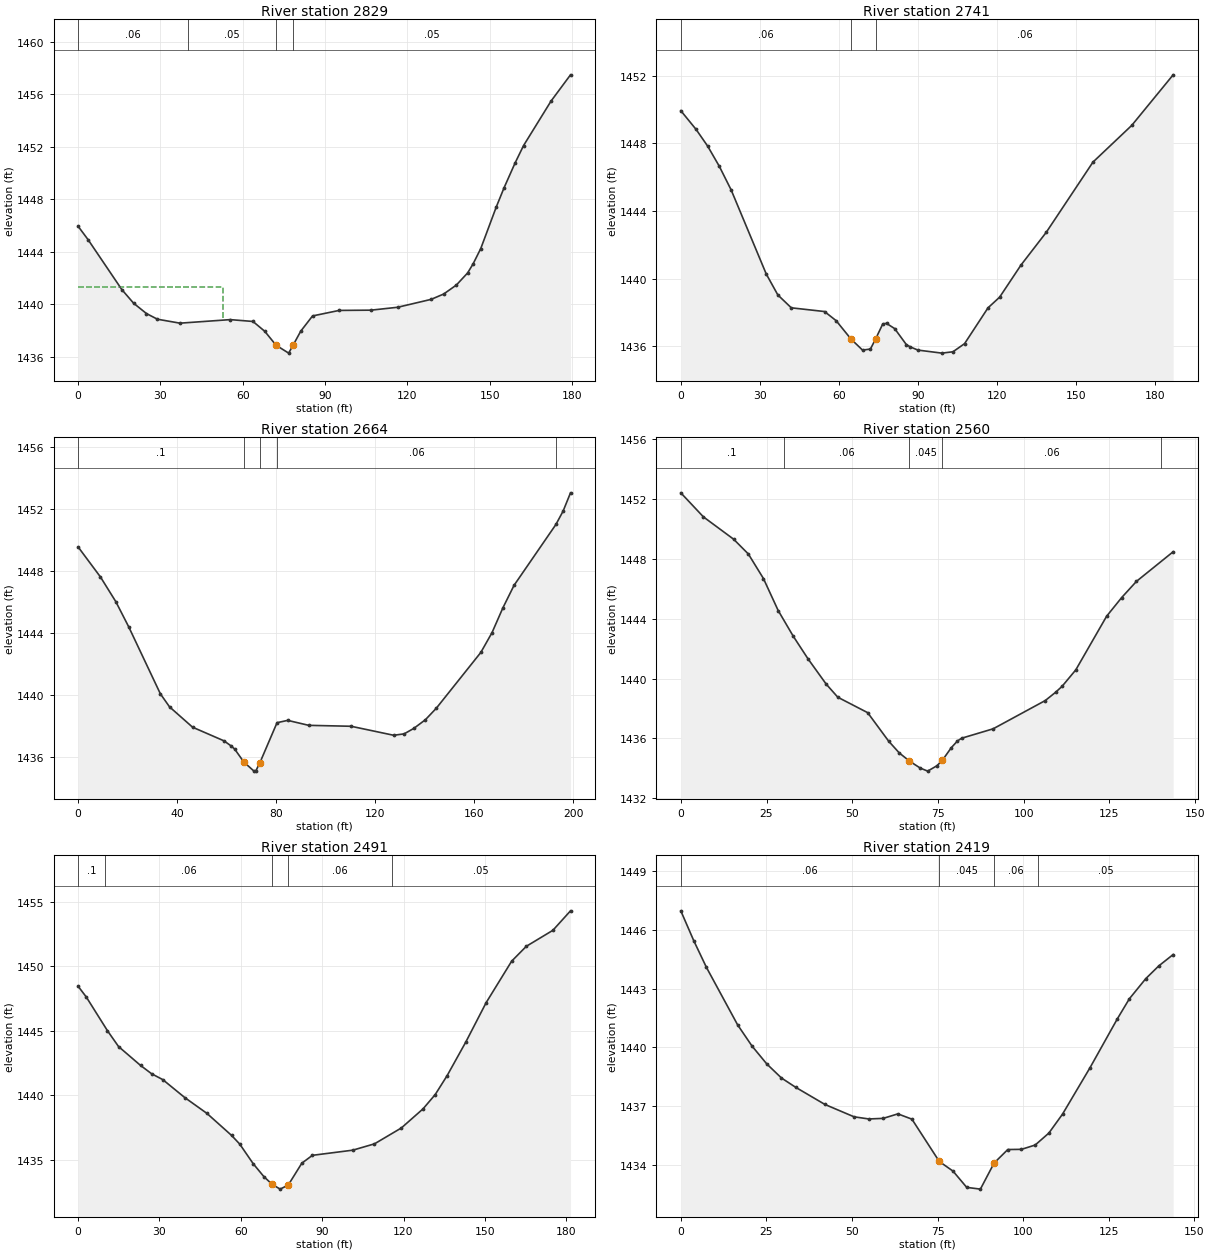
Type RM Length L Ch R = 1 ,2829    ,88.2,88.2,88.2
XS GIS Cut Line= 3
2197049.54542405 750463.204182062197181.39249924750407.312487141
 2197209.3383467 750384.38256102
#Sta/Elev= 30
       0 1445.94     3.6 1444.93    15.9 1441.13    20.2 1440.09    24.9  1439.3
    28.9 1438.87    37.1 1438.57    55.4 1438.84    63.7  1438.7      68 1437.95
    72.11436.893    76.7 1436.29    78.31436.887    81.1 1437.96    85.4 1439.12
    95.1 1439.54   106.7 1439.56   116.4 1439.78   128.6 1440.38   133.2 1440.79
   137.8 1441.47   141.9 1442.39   143.9 1443.08   146.7 1444.25   152.4 1447.44
   155.2 1448.88   159.2 1450.76   162.3 1452.09   172.3 1455.47   179.4 1457.47
#Mann= 4 ,-1,0
       0     .06       0      40     .05       0    72.1    .045       0
    78.3     .05       0
#XS Ineff= 2 , 0
           52.85  1441.3
Permanent Ineff=
       F       F
Bank Sta=72.1,78.3
XS Rating Curve= 0 ,0
Exp/Cntr(USF)=0,0
Exp/Cntr=0.3,0.1

Type RM Length L Ch R = 1 ,2741    ,75.8,76.6,77.2
XS GIS Cut Line= 2
2197082.94931181 750547.807575542197251.62594747750467.716511127
#Sta/Elev= 30
       0 1449.94     5.8 1448.83    10.2 1447.84    14.6 1446.65    19.1 1445.25
    32.4 1440.28    36.8 1439.04    41.9 1438.28    54.5 1438.06    58.9 1437.52
    64.5 1436.44    68.9 1435.78    71.9 1435.84    73.91436.449    76.6 1437.33
      78 1437.36    81.1 1437.05    85.5 1436.11      87 1435.97    89.9 1435.78
      99  1435.6   103.2 1435.68   107.6 1436.16   116.5 1438.28   120.9 1438.91
     129 1440.81   138.6 1442.75   156.3  1446.9     171 1449.07   186.7 1452.06
#Mann= 3 ,-1,0
       0     .06       0    64.5    .045       0    73.9     .06       0
Bank Sta=64.5,73.9
XS Rating Curve= 0 ,0
Exp/Cntr(USF)=0,0
Exp/Cntr=0.3,0.1

Type RM Length L Ch R = 1 ,2664    ,104.5,104.5,104
XS GIS Cut Line= 3
2197109.09561235750613.6690117132197241.67372226750563.364551573
2197292.44831754750537.507118791
#Sta/Elev= 30
       0 1449.54       9 1447.61    15.2 1446.02    20.4  1444.4    33.2 1440.08
    36.9 1439.24    46.2 1437.93    58.9 1437.05    61.7 1436.73    63.2 1436.52
    66.91435.686      71  1435.1    71.7  1435.1    73.4 1435.65    80.3 1438.22
    84.6 1438.37    93.1 1438.05   110.2 1437.99   127.4 1437.41   131.6  1437.5
   135.5 1437.85   140.2 1438.41   144.6 1439.15   162.6 1442.75   167.1 1444.02
   171.5 1445.62     176 1447.07   192.9 1450.99   195.8 1451.85   198.8 1453.03
#Mann= 5 ,-1,0
       0      .1       0    66.9    .045       0    73.4      .1       0
    80.3     .06       0   192.9     .05       0
Bank Sta=66.9,73.4
XS Rating Curve= 0 ,0
Exp/Cntr(USF)=0,0
Exp/Cntr=0.3,0.1

Type RM Length L Ch R = 1 ,2560    ,69.4,68.7,68.1
XS GIS Cut Line= 2
2197158.06793418750706.7288453732197289.91858042750649.959817131
#Sta/Elev= 30
       0 1452.42     6.6 1450.81    15.4 1449.32    19.7 1448.33    24.1 1446.69
    28.4 1444.55    32.8 1442.83    37.1 1441.32    42.4 1439.63    45.8 1438.75
    54.5 1437.72    60.6 1435.82    63.7 1435.03    66.7 1434.48    69.8 1434.02
      72 1433.81    74.7 1434.17    76.3 1434.54    78.9 1435.38    80.7 1435.83
    81.9 1436.01    91.1 1436.64   106.3 1438.53   109.3 1439.08   111.2 1439.48
   115.2 1440.58   124.2 1444.17   128.6 1445.42   132.9  1446.5   143.6 1448.48
#Mann= 5 ,-1,0
       0      .1       0      30     .06       0    66.7    .045       0
    76.3     .06       0     140     .05       0
Bank Sta=66.7,76.3
XS Rating Curve= 0 ,0
Exp/Cntr(USF)=0,0
Exp/Cntr=0.3,0.1

Type RM Length L Ch R = 1 ,2491    ,68,71.9,75.3
XS GIS Cut Line= 4
2197177.60238794750761.3837473092197232.20993186750750.462238525
2197307.44699237750712.8437082712197341.42501969750688.573688751
#Sta/Elev= 30
       0 1448.43       3  1447.6    10.8 1444.99    14.9 1443.76      23  1442.3
    27.1 1441.65    31.2  1441.2    39.3 1439.81    47.5 1438.58    56.6 1436.87
    59.6  1436.2    64.6 1434.67    68.5 1433.68    71.5 1433.09    74.5 1432.71
    77.5 1433.03    82.5 1434.72    86.4 1435.33   101.3 1435.73   109.3 1436.22
   119.2 1437.45   127.2 1438.93   131.7 1440.04   136.1 1441.51     143 1444.12
   150.5 1447.17   159.9 1450.38   165.3 1451.53   175.1 1452.77   181.6 1454.28
#Mann= 5 ,-1,0
       0      .1       0      10     .06       0    71.5    .045       0
    77.5     .06       0  115.69     .05       0
Bank Sta=71.5,77.5
XS Rating Curve= 0 ,0
Exp/Cntr(USF)=0,0
Exp/Cntr=0.3,0.1

Type RM Length L Ch R = 1 ,2419    ,60.6,58.2,55.1
XS GIS Cut Line= 3
 2197188.5889171750831.2544557092197249.02046329750809.279348003
 2197328.3750189750805.006410393
#Sta/Elev= 30
       0 1446.97     3.8 1445.44     7.5 1444.08    16.6 1441.15    20.8 1440.07
    25.1 1439.16    29.4 1438.44    33.6 1437.96    42.1 1437.09    50.6 1436.46
    54.9 1436.35    59.1 1436.38    63.4 1436.61    67.5 1436.34    75.5 1434.18
    79.5 1433.69    83.5 1432.86    87.5 1432.77    91.5  1434.1    95.5 1434.79
    99.5  1434.8   103.5 1435.02   107.5 1435.63   111.5  1436.6   119.5 1438.96
   127.5 1441.46     131 1442.48   135.8 1443.51   139.6 1444.16   143.8 1444.74
#Mann= 4 ,-1,0
       0     .06       0    75.5    .045       0    91.5     .06       0
   104.3     .05       0
Bank Sta=75.5,91.5
XS Rating Curve= 0 ,0
Exp/Cntr(USF)=0,0
Exp/Cntr=0.3,0.1

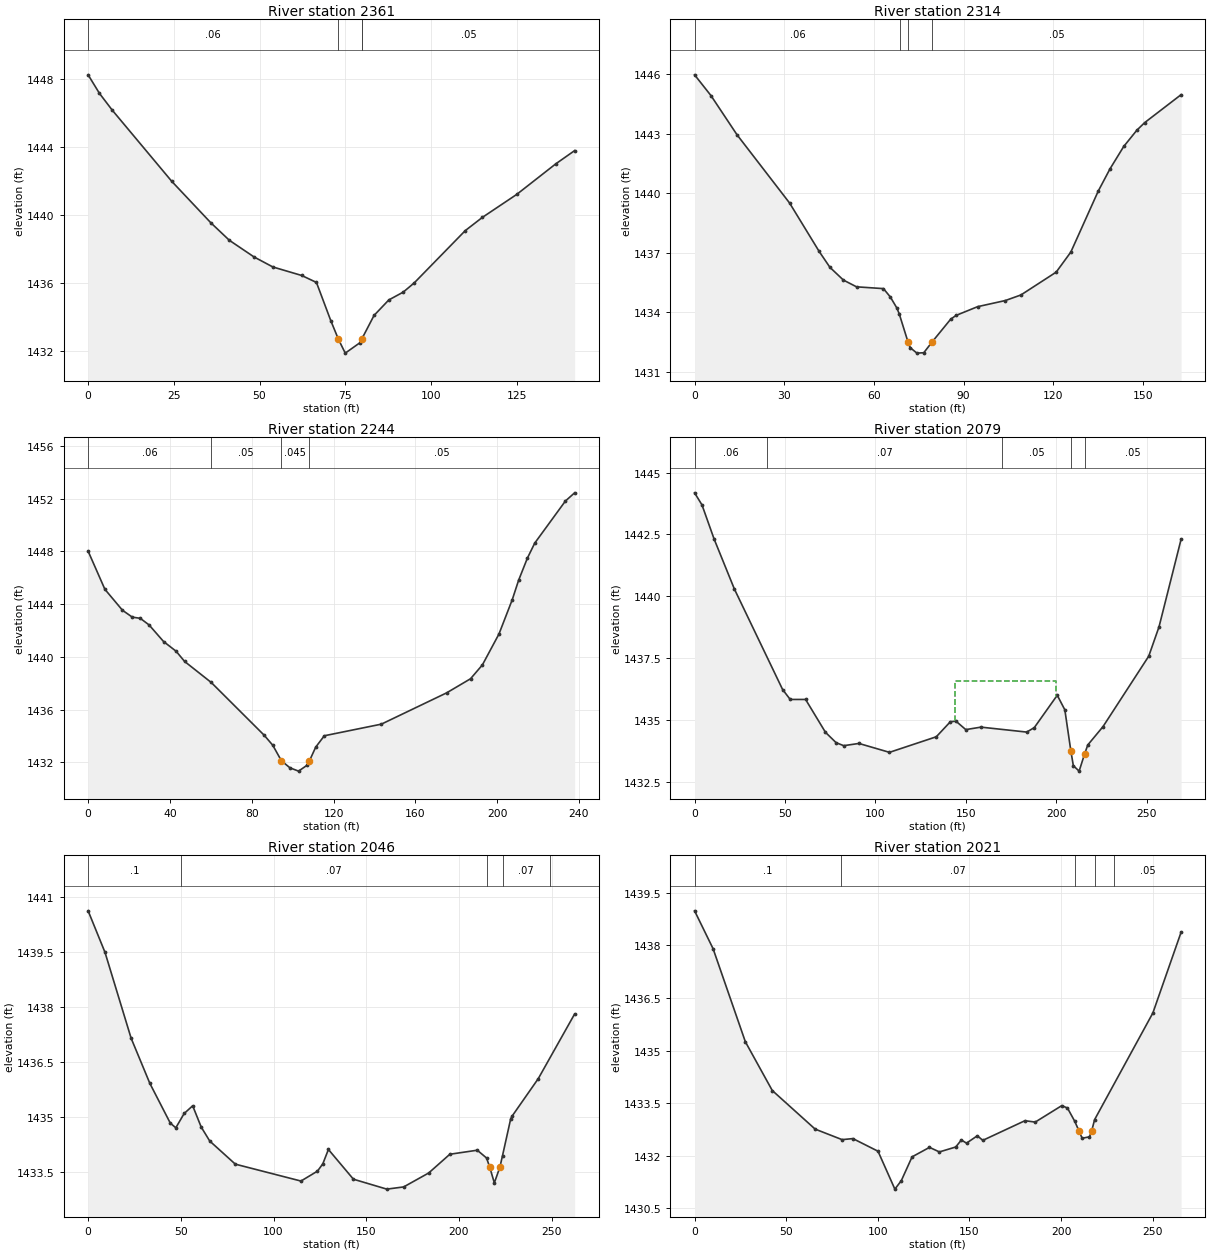
Type RM Length L Ch R = 1 ,2361    ,48.5,47.3,45.8
XS GIS Cut Line= 3
2197205.07024788750887.4130642932197301.51655393750855.060822391
2197333.86879583750831.254455709
#Sta/Elev= 25
       0 1448.26     3.3 1447.17       7 1446.19    24.4 1441.99    35.8 1439.55
    41.2 1438.52    48.4 1437.54    53.9 1436.95    62.3 1436.45    66.6 1436.04
    70.8 1433.78   73.02 1432.69      75 1431.88    79.2 1432.48    79.81432.705
      80 1432.78    83.4  1434.1    87.7 1435.01    91.9 1435.47    95.1 1436.01
     110 1439.09     115 1439.87     125 1441.22   136.4 1443.02   141.9  1443.8
#Mann= 4 ,-1,0
       0     .06       0   73.02    .045       0    79.8     .06       0
      80     .05       0
Bank Sta=73.02,79.8
XS Rating Curve= 0 ,0
Exp/Cntr(USF)=0,0
Exp/Cntr=0.3,0.1

Type RM Length L Ch R = 1 ,2314    ,67.5,69.6,99.4
XS GIS Cut Line= 4
2197227.13372947750939.4419821152197253.57480053750927.833707016
2197318.06521775750894.9435942372197360.62889311750850.445206359
#Sta/Elev= 30
       0 1445.96     5.5 1444.91    14.2 1442.94    31.8  1439.5    41.7 1437.06
    45.3 1436.26    49.8 1435.62    54.2 1435.28    63.2 1435.19    65.5 1434.77
    67.7 1434.21    68.5 1433.91    71.4 1432.51    72.2 1432.21    74.4 1431.94
    76.7 1431.96    79.51432.506    85.7 1433.65    87.5 1433.84    94.7 1434.28
     104 1434.59   109.2 1434.87     121 1436.02   125.9 1437.03   135.1 1440.11
     139 1441.22   143.6 1442.35     148 1443.17   150.6 1443.55   162.8 1444.96
#Mann= 4 ,-1,0
       0     .06       0   68.88     .05       0    71.4    .045       0
    79.5     .05       0
Bank Sta=71.4,79.5
XS Rating Curve= 0 ,0
Exp/Cntr(USF)=0,0
Exp/Cntr=0.3,0.1

Type RM Length L Ch R = 1 ,2244    ,163.4,164.8,128.7
XS GIS Cut Line= 4
2197228.63807113751005.9129929252197305.25268678750973.990236403
2197362.71364852750955.4169962462197443.97157421750907.242654586
#Sta/Elev= 30
       0 1448.01     8.2 1445.12    16.8 1443.53    21.6 1443.01    25.5 1442.92
    29.8 1442.42    36.9 1441.16      43 1440.43    47.2 1439.65    60.2 1438.06
    86.1 1434.06    90.3  1433.3    94.5 1432.13    98.7 1431.59   102.9 1431.34
   107.1 1431.79   108.2 1432.11   111.3 1433.16   115.5 1434.02   143.4  1434.9
   175.3 1437.27     187 1438.34   192.8 1439.39   200.9 1441.73   207.4 1444.33
   210.5  1445.8   214.8 1447.48   218.4 1448.62   233.4 1451.81   237.9 1452.43
#Mann= 4 ,-1,0
       0     .06       0      60     .05       0    94.5    .045       0
   108.2     .05       0
Bank Sta=94.5,108.2
XS Rating Curve= 0 ,0
Exp/Cntr(USF)=0,0
Exp/Cntr=0.3,0.1

Type RM Length L Ch R = 1 ,2079    ,34.4,33.6,32.6
XS GIS Cut Line= 2
  2197245.968365751096.1765875042197501.12378226751010.717835312
#Sta/Elev= 30
       0 1444.18     4.1 1443.69    10.8 1442.31      22 1440.29    48.7 1436.22
    52.9 1435.82    61.4 1435.82    72.4 1434.49    78.3 1434.07    82.5 1433.95
    90.9 1434.04   107.8 1433.68   133.7 1434.31   141.5 1434.92   144.6 1434.94
     150  1434.6   158.4  1434.7   183.7  1434.5   187.9 1434.68   200.6 1435.99
   204.8  1435.4   208.1 1433.75   209.5 1433.14   212.7 1432.92   215.8 1433.63
   217.5 1433.98   225.9 1434.72   251.2 1437.57   256.9 1438.76   269.1  1442.3
#Mann= 5 ,-1,0
       0     .06       0      40     .07       0     170     .05       0
   208.1    .045       0   215.8     .05       0
#XS Ineff= 1 ,-1
   144.2  200.09 1436.57
Permanent Ineff=
       F
Bank Sta=208.1,215.8
XS Rating Curve= 0 ,0
Exp/Cntr(USF)=0,0
Exp/Cntr=0.3,0.1

Type RM Length L Ch R = 1 ,2046    ,110.4,25.3,25.3
XS GIS Cut Line= 5
2197263.22699102751164.7116929682197356.67613654 751111.31218124
2197439.00038379751068.5925718582197465.25514372751057.022677651
2197494.17987924751040.557828201
#Sta/Elev= 30
       0 1440.62     9.1 1439.49    23.2 1437.15    33.3 1435.92    44.3 1434.84
    47.3 1434.71    51.8  1435.1    56.4 1435.31      61 1434.73    65.6 1434.35
    79.4 1433.72   114.8 1433.26   123.7 1433.53   126.6 1433.73   129.6 1434.12
   143.1 1433.31   161.1 1433.04   170.2  1433.1   183.7 1433.48   195.1 1433.99
   209.9  1434.1   214.91433.888  216.66 1433.63   219.1 1433.21   222.1 1433.64
   223.5 1433.95   227.9 1434.95   228.7 1435.03   242.8 1436.05   262.4 1437.81
#Mann= 5 ,-1,0
       0      .1       0      50     .07       0   214.9    .045       0
   223.5     .07       0  249.07     .05       0
Bank Sta=216.66,222.1
XS Rating Curve= 0 ,0
Exp/Cntr(USF)=0,0
Exp/Cntr=0.3,0.1

Type RM Length L Ch R = 1 ,2021    ,27.9,120,122.9
XS GIS Cut Line= 6
2197277.24436285751180.0640525892197370.69350837751126.664540862
2197453.01775562 751083.944931482197471.70758472 751083.94493148
2197478.82751962751075.0450128592197508.19725107751055.910187823
#Sta/Elev= 30
       0 1438.98    10.1  1437.9    27.7 1435.25    42.4 1433.86    65.8 1432.76
    80.5 1432.46    86.4 1432.49   100.1 1432.13   109.3 1431.05   112.8 1431.29
   118.7 1431.97   128.2 1432.24   133.6 1432.11   142.5 1432.25   145.6 1432.45
   148.4 1432.36   154.3 1432.57   157.3 1432.44   180.3    1433   185.9 1432.96
   200.4 1433.43   203.5 1433.36   207.5 1432.98  209.83  1432.7   211.5  1432.5
   215.5 1432.54   216.71432.706   218.3 1433.03   250.1 1436.07   265.5 1438.37
#Mann= 5 ,-1,0
       0      .1       0      80     .07       0   207.5    .045       0
   218.3     .07       0  229.07     .05       0
Bank Sta=209.83,216.7
XS Rating Curve= 0 ,0
Exp/Cntr(USF)=0,0
Exp/Cntr=0.3,0.1

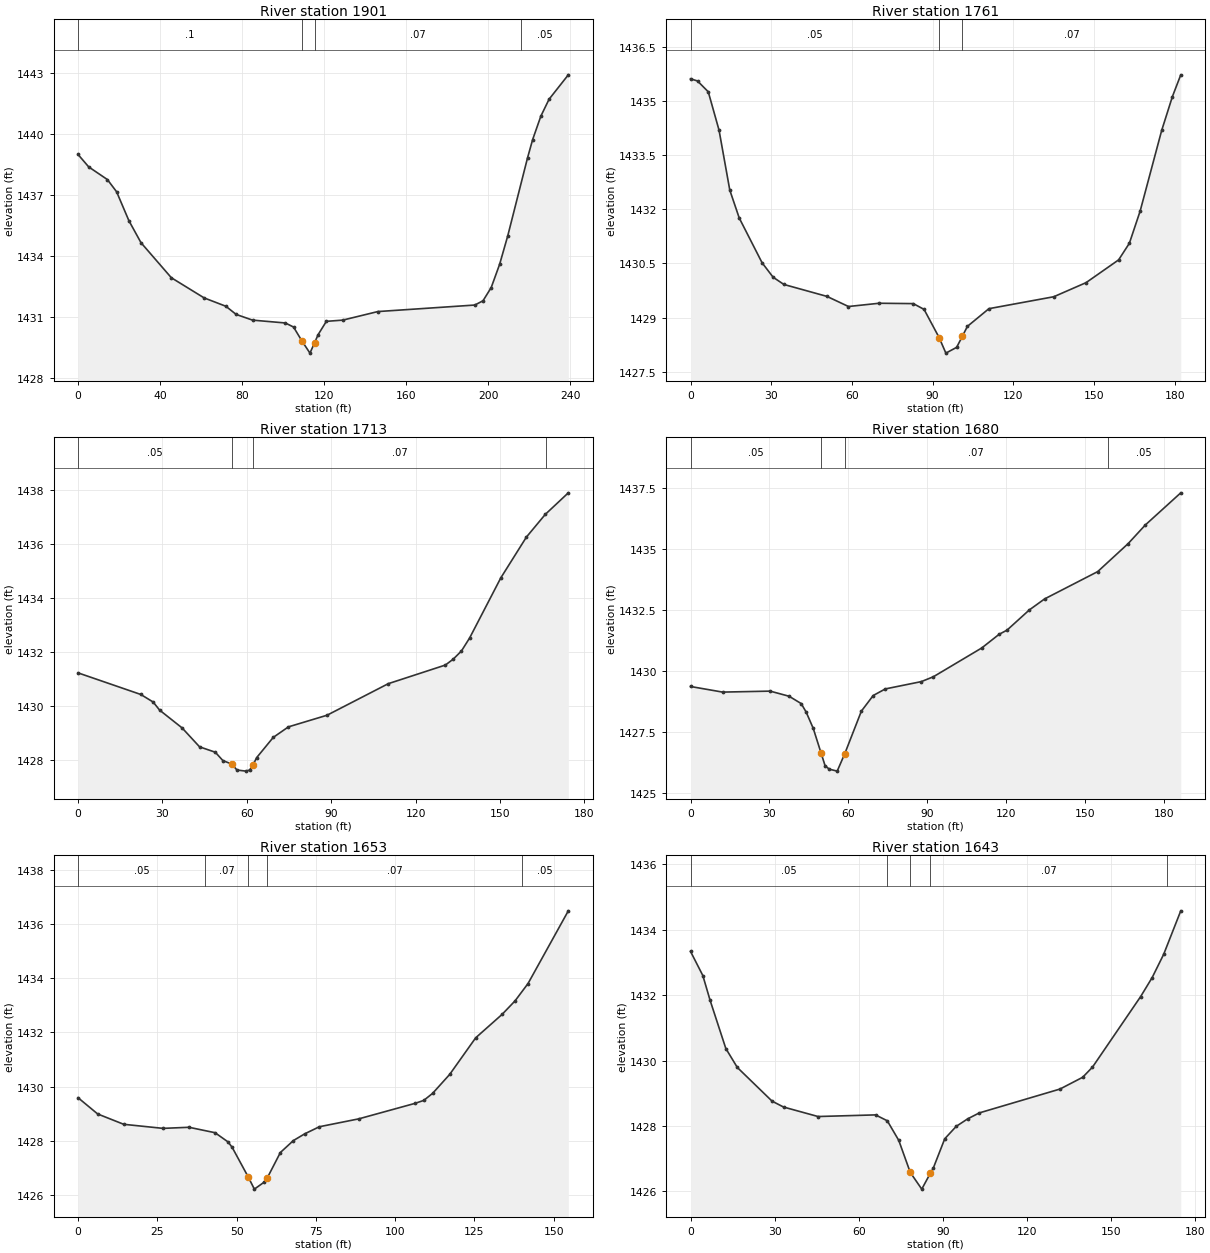
Type RM Length L Ch R = 1 ,1901    ,140.5,140,139.6
XS GIS Cut Line= 4
2197275.59503483751186.1892689892197339.17068846751152.195237161
2197413.28912723751149.9895202642197505.45879536751161.134006712
#Sta/Elev= 30
       0 1438.99     5.2 1438.38    14.3 1437.76    18.8 1437.16    24.8 1435.74
    30.7 1434.66    45.5 1432.94    61.5 1431.95    72.1 1431.54    77.1 1431.14
    85.1 1430.86   101.1 1430.72   105.1 1430.52   109.1 1429.85   113.1 1429.24
   115.4 1429.76   117.1 1430.15   121.1  1430.8   129.1 1430.86   146.2 1431.28
   193.5  1431.6   197.5 1431.81   201.5 1432.46   205.6  1433.6   209.6 1435.01
   219.2 1438.82   221.7 1439.72   225.7 1440.87   229.7  1441.7   239.1  1442.9
#Mann= 4 ,-1,0
       0      .1       0   109.1    .045       0   115.4     .07       0
  216.24     .05       0
Bank Sta=109.1,115.4
XS Rating Curve= 0 ,0
Exp/Cntr(USF)=0,0
Exp/Cntr=0.3,0.1

Type RM Length L Ch R = 1 ,1761    ,52,48,42.3
XS GIS Cut Line= 2
2197285.61701063751298.1192451432197467.28651593751283.608901269
#Sta/Elev= 28
       0 1435.61     2.6 1435.55     6.6 1435.25    10.6 1434.19    14.6 1432.53
    18.1 1431.76    26.6 1430.52    30.7 1430.12    34.7 1429.92    50.7 1429.59
    58.7 1429.31    70.1  1429.4    82.8 1429.39    86.8 1429.23    92.4 1428.45
    94.9 1428.02    98.9 1428.18     1011428.481   102.9 1428.76   110.9 1429.25
     135 1429.58     147 1429.97   159.1  1430.6   163.1 1431.06   167.1 1431.95
   175.1 1434.18   179.1 1435.12   182.2 1435.72
#Mann= 3 ,-1,0
       0     .05       0    92.4    .045       0     101     .07       0
Bank Sta=92.4,101
XS Rating Curve= 0 ,0
Exp/Cntr(USF)=0,0
Exp/Cntr=0.3,0.1

Type RM Length L Ch R = 1 ,1713    ,32.1,32.2,33.2
XS GIS Cut Line= 4
2197337.31492001751369.6422749232197350.57489669751357.389124427
2197419.07754726751319.407456786 2197484.1889775 751276.67808069
#Sta/Elev= 26
       0 1431.24    22.3 1430.44    26.7 1430.16      29 1429.86      37  1429.2
    43.2  1428.5    48.8  1428.3    51.5 1427.99    54.7 1427.86    56.5 1427.64
    59.7  1427.6      61 1427.64   62.27 1427.84    63.5  1428.1    69.4 1428.85
    74.8 1429.24    88.5 1429.67   110.3 1430.84   130.6 1431.53   133.4 1431.75
   136.3 1432.05   139.2 1432.53   150.3 1434.76   159.4 1436.27   166.1 1437.11
   174.3 1437.91
#Mann= 4 ,-1,0
       0     .05       0    54.7    .045       0   62.27     .07       0
  166.38     .05       0
Bank Sta=54.7,62.27
XS Rating Curve= 0 ,0
Exp/Cntr(USF)=0,0
Exp/Cntr=0.3,0.1

Type RM Length L Ch R = 1 ,1680    ,25.2,27.4,30.5
XS GIS Cut Line= 4
2197346.92683212751401.2814856212197369.87260204751381.489659125
2197438.37525261751343.5079914842197503.48668285751300.778615388
#Sta/Elev= 26
       0 1429.35    12.2 1429.12    30.3 1429.16    37.5 1428.95    42.1 1428.65
      44  1428.3    46.7 1427.63    49.7 1426.61    51.2  1426.1    52.8 1425.96
    55.8 1425.88    58.7  1426.6      65 1428.34    69.5 1428.98    74.1 1429.25
    87.8 1429.55    92.4 1429.75   110.8 1430.93   117.4 1431.49   120.4 1431.66
   128.9 1432.49   134.7 1432.94   154.9 1434.06   166.5 1435.21     173 1435.97
   186.5 1437.29
#Mann= 4 ,-1,0
       0     .05       0    49.7    .045       0    58.7     .07       0
  158.63     .05       0
Bank Sta=49.7,58.7
XS Rating Curve= 0 ,0
Exp/Cntr(USF)=0,0
Exp/Cntr=0.3,0.1

Type RM Length L Ch R = 1 ,1653    ,10.5,10.3,10.3
XS GIS Cut Line= 2
2197342.12087607751409.691908718 2197492.5120292751374.002977315
#Sta/Elev= 26
       0 1429.59     6.2 1428.99    14.4 1428.61    26.8 1428.46      35  1428.5
    43.2  1428.3    47.3 1427.96    48.6 1427.76    53.61426.682    55.6 1426.22
    58.6 1426.47    59.7 1426.64    63.8 1427.57    67.9 1428.01    71.5 1428.26
    76.1 1428.52    88.5 1428.81   106.2 1429.38     109 1429.49   111.8 1429.75
   117.2 1430.45   125.4  1431.8   133.7 1432.66   137.8 1433.16   141.9  1433.8
   154.6 1436.48
#Mann= 5 ,-1,0
       0     .05       0      40     .07       0    53.6    .045       0
    59.7     .07       0     140     .05       0
Bank Sta=53.6,59.7
XS Rating Curve= 0 ,0
Exp/Cntr(USF)=0,0
Exp/Cntr=0.3,0.1

Type RM Length L Ch R = 1 ,1643    ,15.3,15.7,16.5
XS GIS Cut Line= 2
2197319.87917097751425.2946489192197490.11843128751385.278249083
#Sta/Elev= 26
       0 1433.34     4.4  1432.6       7 1431.84    12.6 1430.37    16.7 1429.79
    29.1 1428.76    33.2 1428.58    45.5 1428.29      66 1428.34    70.2 1428.16
    74.3 1427.56    78.4 1426.58    82.5 1426.07    85.61426.562    86.6 1426.71
    90.7 1427.61    94.8 1427.99    98.9 1428.22     103  1428.4   131.8 1429.13
   139.9 1429.49   143.4  1429.8   160.6 1431.96   164.7 1432.54   168.8 1433.25
   174.9 1434.58
#Mann= 5 ,-1,0
       0     .05       0      70     .07       0    78.4    .045       0
    85.6     .07       0     170     .05       0
Bank Sta=78.4,85.6
XS Rating Curve= 0 ,0
Exp/Cntr(USF)=0,0
Exp/Cntr=0.3,0.1

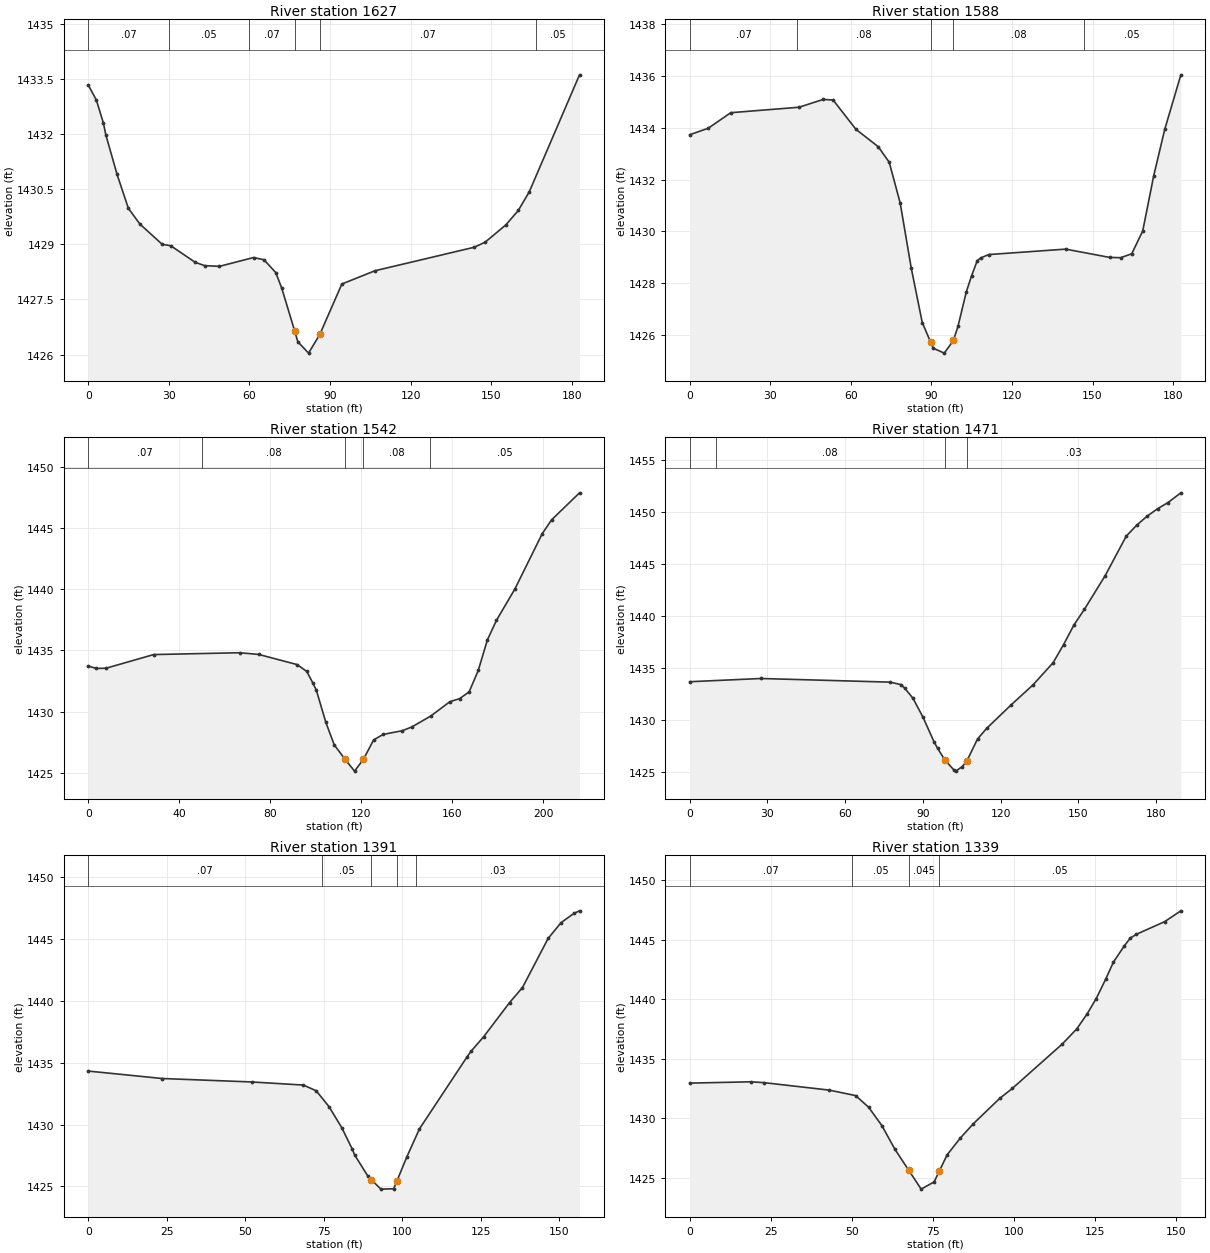
Type RM Length L Ch R = 1 ,1627    ,40,39.4,38.1
XS GIS Cut Line= 3
2197326.06448554751446.1423454282197389.14118359751424.438535348
2197502.40794244751398.665260877
#Sta/Elev= 28
       0 1433.33       3 1432.92     5.6  1432.3     6.5 1431.98    10.7  1430.9
    14.9 1429.98    19.2 1429.55    27.5    1429    30.7 1428.96    39.8 1428.51
    43.3 1428.42    48.8  1428.4    61.5 1428.64    65.4 1428.58    69.8 1428.23
      72 1427.81    76.81426.651      78 1426.35      82 1426.04    86.2 1426.55
    94.4 1427.92   106.7 1428.28   143.7 1428.92   147.8 1429.06   155.5 1429.53
   160.1 1429.92   164.2 1430.43   182.9 1433.61
#Mann= 6 ,-1,0
       0     .07       0      30     .05       0      60     .07       0
    76.8    .045       0    86.2     .07       0  166.71     .05       0
Bank Sta=76.8,86.2
XS Rating Curve= 0 ,0
Exp/Cntr(USF)=0,0
Exp/Cntr=0.3,0.1

Type RM Length L Ch R = 1 ,1588    ,46.5,45.7,44.7
XS GIS Cut Line= 3
2197341.66409904751477.3415724192197404.74079708751455.637762338
2197518.00755594751429.864487868
#Sta/Elev= 30
       0 1433.73     6.9 1433.98    15.3 1434.58    40.7 1434.79    49.7 1435.09
    53.4 1435.07    61.9 1433.94    70.2 1433.27    74.3 1432.67    78.4 1431.09
    82.5 1428.59    86.6 1426.49    89.7 1425.74    90.7  1425.5    94.8 1425.31
    98.21425.798    99.9 1426.34     103 1427.67     105  1428.3   107.1 1428.88
   108.4 1428.98   111.3 1429.11     140 1429.32   156.4    1429   160.5 1428.99
   164.6 1429.14   168.7 1430.02   172.8 1432.15   176.9 1433.94   182.9 1436.04
#Mann= 5 ,-1,0
       0     .07       0      40     .08       0    89.7    .045       0
    98.2     .08       0  146.71     .05       0
Bank Sta=89.7,98.2
XS Rating Curve= 0 ,0
Exp/Cntr(USF)=0,0
Exp/Cntr=0.3,0.1

Type RM Length L Ch R = 1 ,1542    ,70.5,70.5,70.3
XS GIS Cut Line= 3
 2197340.8211696751525.8507993392197499.73829647751474.789250893
 2197548.3936181751469.481397624
#Sta/Elev= 30
       0 1433.72     3.5 1433.53     7.7 1433.54    28.7 1434.66    66.5 1434.81
    74.9 1434.67    91.8 1433.84      96 1433.28    98.6 1432.37   100.2 1431.76
   104.4 1429.12   108.1 1427.28   112.8 1426.12     117 1425.14   120.9  1426.1
   125.4 1427.69   129.6 1428.14     138 1428.44   142.2 1428.75   150.6 1429.65
   158.9 1430.81   163.2 1431.06   167.4 1431.62   171.4 1433.37   175.4 1435.86
   179.4 1437.46   187.5 1440.02   199.5 1444.53   203.6 1445.66   215.9 1447.87
#Mann= 5 ,-1,0
       0     .07       0      50     .08       0   112.8    .045       0
   120.9     .08       0     150     .05       0
Bank Sta=112.8,120.9
XS Rating Curve= 0 ,0
Exp/Cntr(USF)=0,0
Exp/Cntr=0.3,0.1

Type RM Length L Ch R = 1 ,1471    ,79.9,80.7,81.6
XS GIS Cut Line= 4
2197377.43188033751584.2184483172197432.33547048751570.891642941
2197504.41742845751546.8643236172197561.20927412751540.311418347
#Sta/Elev= 29
       0 1433.66    27.5 1433.97    77.4 1433.62    81.6 1433.38      83 1433.04
    86.2 1432.07    90.1 1430.23    94.3  1427.9    95.7 1427.2698.458891426.157
     102 1425.18   102.7 1425.07   105.2  1425.5106.95891426.032   111.1 1428.15
   114.6 1429.17   124.1 1431.44   132.5 1433.35   140.3 1435.49   144.3 1437.22
   148.3  1439.1   152.4 1440.63   160.4 1443.86   168.5 1447.64   172.5 1448.69
   176.5 1449.55   180.6 1450.28   184.6 1450.87   189.6 1451.81
#Mann= 4 ,-1,0
       0     .05       0      10     .08       098.45889    .045       0
106.9589     .03       0
Bank Sta=98.45889,106.9589
XS Rating Curve= 0 ,0
Exp/Cntr(USF)=0,0
Exp/Cntr=0.3,0.1

Type RM Length L Ch R = 1 ,1391    ,50.6,51.4,52.3
XS GIS Cut Line= 3
2197404.99857505751653.1351850962197438.88837575751647.342204424
2197557.93282149751620.038432466
#Sta/Elev= 25
       0 1434.32    23.5 1433.72    52.1 1433.44    68.5 1433.19    72.6 1432.73
    76.7 1431.44    80.8 1429.72      84 1428.06    84.9 1427.52    89.1 1425.82
90.218571425.536    93.2 1424.78    97.3 1424.8198.318581425.436   101.4 1427.34
   105.5 1429.65   120.7 1435.48   121.9 1435.91     126 1437.11   134.2 1439.85
   138.3 1441.06   146.5 1445.04   150.6 1446.31   154.7 1447.06   156.5 1447.27
#Mann= 5 ,-1,0
       0     .07       0   74.38     .05       090.21857    .045       0
98.31858     .05       0  104.38     .03       0
Bank Sta=90.21857,98.31858
XS Rating Curve= 0 ,0
Exp/Cntr(USF)=0,0
Exp/Cntr=0.3,0.1

Type RM Length L Ch R = 1 ,1339    ,55.2,57,59.3
XS GIS Cut Line= 3
2197433.45565966751694.4874137352197533.77408644  751680.9523879
2197571.99062998751648.309090296
#Sta/Elev= 28
       0 1432.97    18.9 1433.08    22.9 1433.01    43.1 1432.38    51.2 1431.92
    55.2 1430.94    59.3 1429.39    63.3 1427.41    67.61425.632    71.4 1424.06
    75.4 1424.67      771425.578    79.4 1426.94    83.5 1428.36    87.5 1429.56
    95.6 1431.68    99.5 1432.52   114.9 1436.25   119.4 1437.53   122.6 1438.79
   125.4 1440.08   128.3  1441.7   130.7 1443.14     134 1444.48   135.9 1445.16
   137.8 1445.48   146.5 1446.54   151.5 1447.45
#Mann= 4 ,-1,0
       0     .07       0      50     .05       0    67.6    .045       0
      77     .05       0
Bank Sta=67.6,77
XS Rating Curve= 0 ,0
Exp/Cntr(USF)=0,0
Exp/Cntr=0.3,0.1

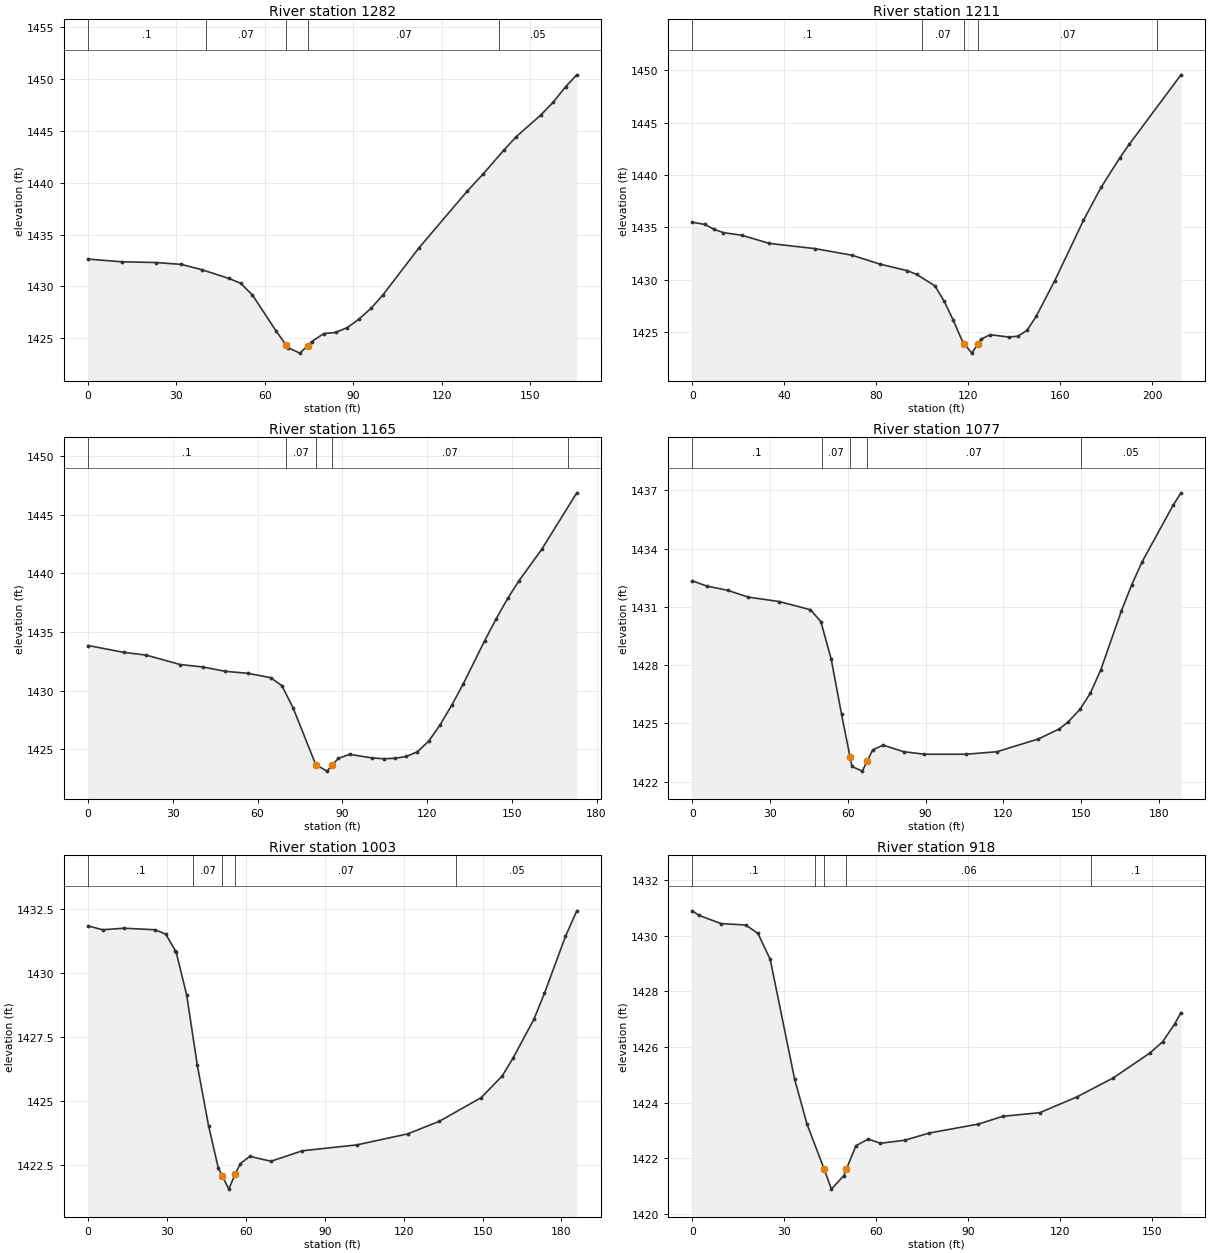
Type RM Length L Ch R = 1 ,1282    ,72.3,71.4,70.4
XS GIS Cut Line= 3
2197440.62126158751734.2963132512197549.69764625751745.442805116
2197603.83774959751760.570186932
#Sta/Elev= 29
       0 1432.63    11.6 1432.37    23.1  1432.3    31.7 1432.12    38.7  1431.6
    47.8 1430.77    51.8  1430.3    55.8 1429.17    63.9 1425.67    67.31424.327
    67.9 1424.09    71.9 1423.57    74.61424.298    75.9 1424.68      80 1425.45
      84 1425.56      88 1426.03      92 1426.86    96.1  1427.9   100.1 1429.18
   112.2 1433.67   128.8 1439.21   134.2 1440.86   141.3 1443.18   145.4 1444.44
   153.6 1446.49   157.9 1447.75   162.1 1449.24   165.9 1450.39
#Mann= 5 ,-1,0
       0      .1       0      40     .07       0    67.3    .045       0
    74.6     .07       0  139.64     .05       0
Bank Sta=67.3,74.6
XS Rating Curve= 0 ,0
Exp/Cntr(USF)=0,0
Exp/Cntr=0.3,0.1

Type RM Length L Ch R = 1 ,1211    ,45.3,45.8,46
XS GIS Cut Line= 3
2197382.65612635751814.4248847022197544.52707355751811.200363842
2197594.18469481751801.526801259
#Sta/Elev= 30
       0 1435.49     5.5 1435.28     9.5 1434.81    13.5  1434.5    21.5 1434.25
    33.5 1433.47    53.5 1432.97    69.5 1432.34    81.5  1431.5    93.5 1430.87
    97.5 1430.52   105.5 1429.42   109.5 1427.96   113.5 1426.13   117.5  1424.1
   118.21423.907   121.5    1423   124.3  1423.9   125.5 1424.32   129.5 1424.76
   137.5 1424.54   141.5 1424.61   145.5 1425.16   149.5  1426.5   157.6 1429.91
   170.1 1435.68   177.8 1438.84     186 1441.67   190.1 1442.96   212.5 1449.56
#Mann= 5 ,-1,0
       0      .1       0     100     .07       0   118.2    .045       0
   124.3     .07       0   201.9     .05       0
Bank Sta=118.2,124.3
XS Rating Curve= 0 ,0
Exp/Cntr(USF)=0,0
Exp/Cntr=0.3,0.1

Type RM Length L Ch R = 1 ,1165    ,88.7,88.5,88.5
XS GIS Cut Line= 2
2197415.59270212751856.480004762 2197588.5449387751857.158248827
#Sta/Elev= 30
       0 1433.84    12.6 1433.26    20.6 1433.02    32.6 1432.22    40.6 1432.01
    48.6 1431.64    56.6 1431.47    64.6  1431.1    68.6 1430.42    72.6 1428.51
    80.6 1423.68    84.6 1423.13   86.47 1423.67    88.6 1424.22    92.6 1424.56
   100.6 1424.25   104.6 1424.19   108.6 1424.22   112.6 1424.38   116.6 1424.78
   120.6 1425.69   124.6 1427.07   128.8 1428.78   132.8 1430.56   140.4 1434.25
   144.5 1436.13   148.6 1437.88   152.6 1439.38   160.6 1442.04     173 1446.86
#Mann= 5 ,-1,0
       0      .1       0      70     .07       0    80.6    .045       0
   86.47     .07       0     170     .05       0
Bank Sta=80.6,86.47
XS Rating Curve= 0 ,0
Exp/Cntr(USF)=0,0
Exp/Cntr=0.3,0.1

Type RM Length L Ch R = 1 ,1077    ,73.2,73.5,73.5
XS GIS Cut Line= 2
2197434.58353594751944.6517332132197623.13538602751944.651733213
#Sta/Elev= 30
       0 1432.34     5.6 1432.07    13.6 1431.85    21.6  1431.5    33.6 1431.27
    45.6 1430.85    49.6 1430.24    53.6 1428.31    57.6 1425.46    60.91423.249
    61.6 1422.78    65.6 1422.54    67.51423.058    69.6 1423.63    73.6 1423.88
    81.6 1423.54    89.6 1423.41   105.6 1423.41   117.6 1423.54   133.6  1424.2
   141.6 1424.71   145.1 1425.08   149.6 1425.72   153.6 1426.55   157.6 1427.74
   165.6 1430.79   169.6 1432.14   173.6 1433.32   185.6 1436.24   188.6 1436.87
#Mann= 5 ,-1,0
       0      .1       0      50     .07       0    60.9    .045       0
    67.5     .07       0     150     .05       0
Bank Sta=60.9,67.5
XS Rating Curve= 0 ,0
Exp/Cntr(USF)=0,0
Exp/Cntr=0.3,0.1

Type RM Length L Ch R = 1 ,1003    ,84.9,84.9,84.4
XS GIS Cut Line= 2
2197442.72246472 752017.223848172197628.56133854  752018.5803363
#Sta/Elev= 28
       0 1431.84     5.5 1431.69    13.5 1431.75    25.5 1431.69    29.5 1431.52
    33.2 1430.87    33.5 1430.81    37.5 1429.13    41.5 1426.41    45.8 1424.03
    49.5 1422.38      511422.069    53.5 1421.55    55.91422.137    57.9 1422.55
    61.5 1422.83    69.5 1422.64    81.5 1423.05   102.2 1423.28   121.5 1423.71
   133.5  1424.2   149.5 1425.13   157.5 1425.98   161.5 1426.66   169.5 1428.19
   173.5  1429.2   181.5 1431.43   185.8 1432.43
#Mann= 5 ,-1,0
       0      .1       0      40     .07       0      51    .045       0
    55.9     .07       0     140     .05       0
Bank Sta=51,55.9
XS Rating Curve= 0 ,0
Exp/Cntr(USF)=0,0
Exp/Cntr=0.3,0.1

Type RM Length L Ch R = 1 ,918     ,36.9,36.9,36.9
XS GIS Cut Line= 2
2197446.79192911752102.0043562972197606.17928439752097.256647842
#Sta/Elev= 26
       0  1430.9     2.1 1430.74     9.4 1430.44    17.4 1430.39    21.4 1430.09
    25.4 1429.16    33.4 1424.84    37.4 1423.24      431421.618    45.4 1420.89
    49.4 1421.37    50.31421.613    53.4 1422.45    57.4 1422.69    61.4 1422.54
    69.4 1422.65    77.4 1422.91    93.4 1423.23   101.4 1423.51   113.4 1423.64
   125.4  1424.2   137.4 1424.89   149.4 1425.79   153.5 1426.19   157.5 1426.84
   159.5 1427.24
#Mann= 5 ,-1,0
       0      .1       0      40     .06       0      43    .045       0
    50.3     .06       0     130      .1       0
Bank Sta=43,50.3
XS Rating Curve= 0 ,0
Exp/Cntr(USF)=0,0
Exp/Cntr=0.3,0.1