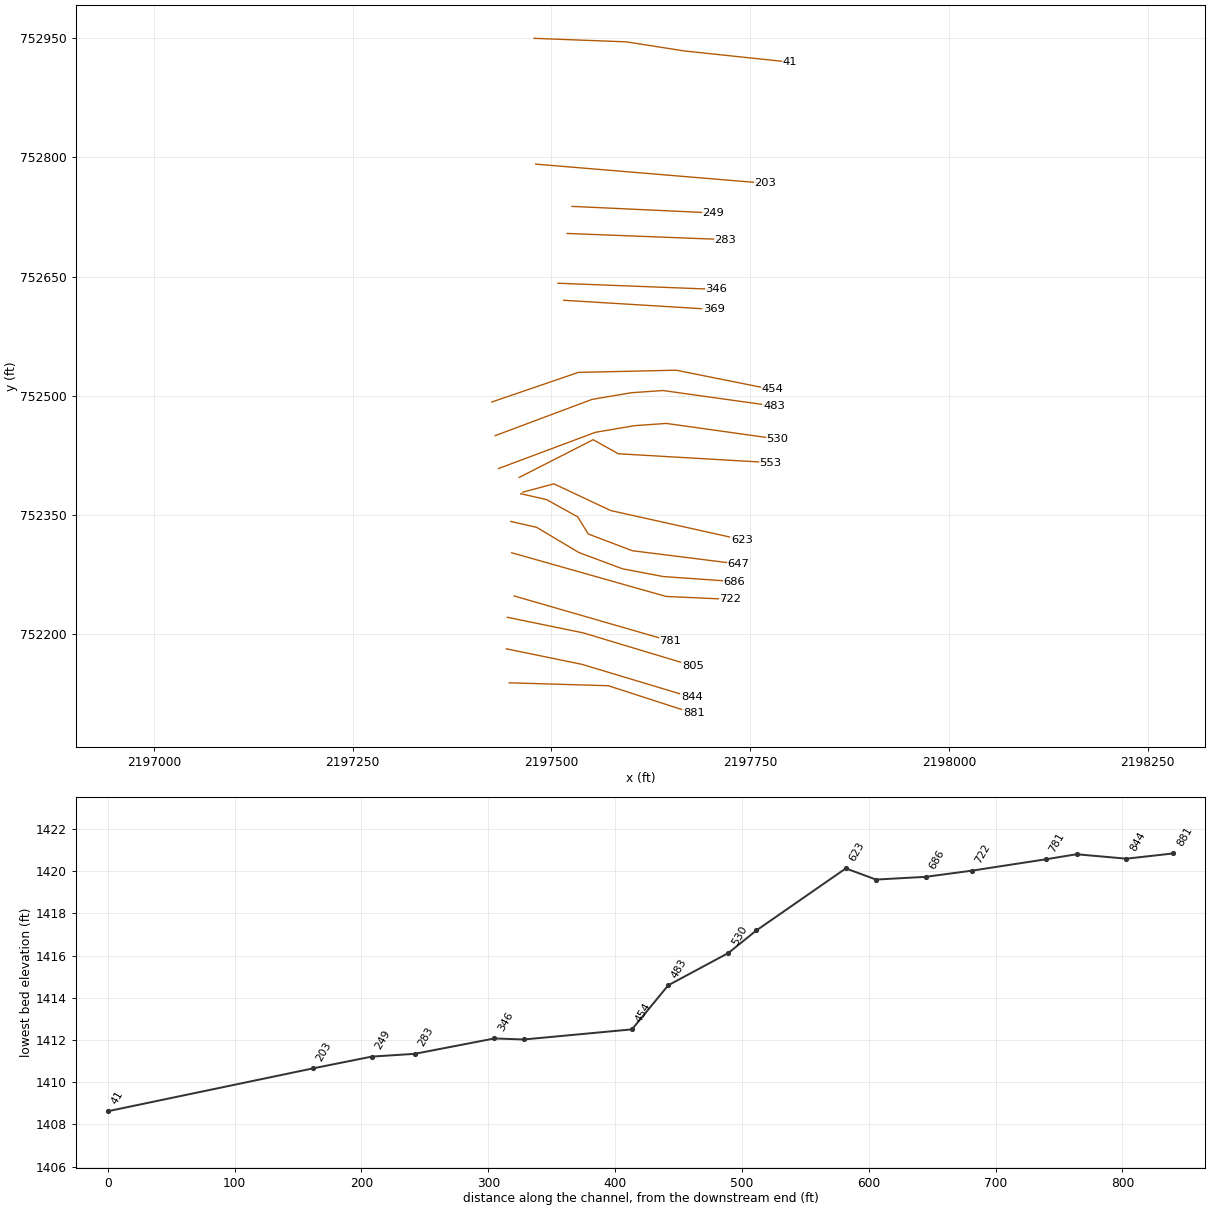
HEC-RAS study PECKSRNT4.prj: PECKSRNT4

--- PECKSRNT4.g01 (geometry) --- (continued)

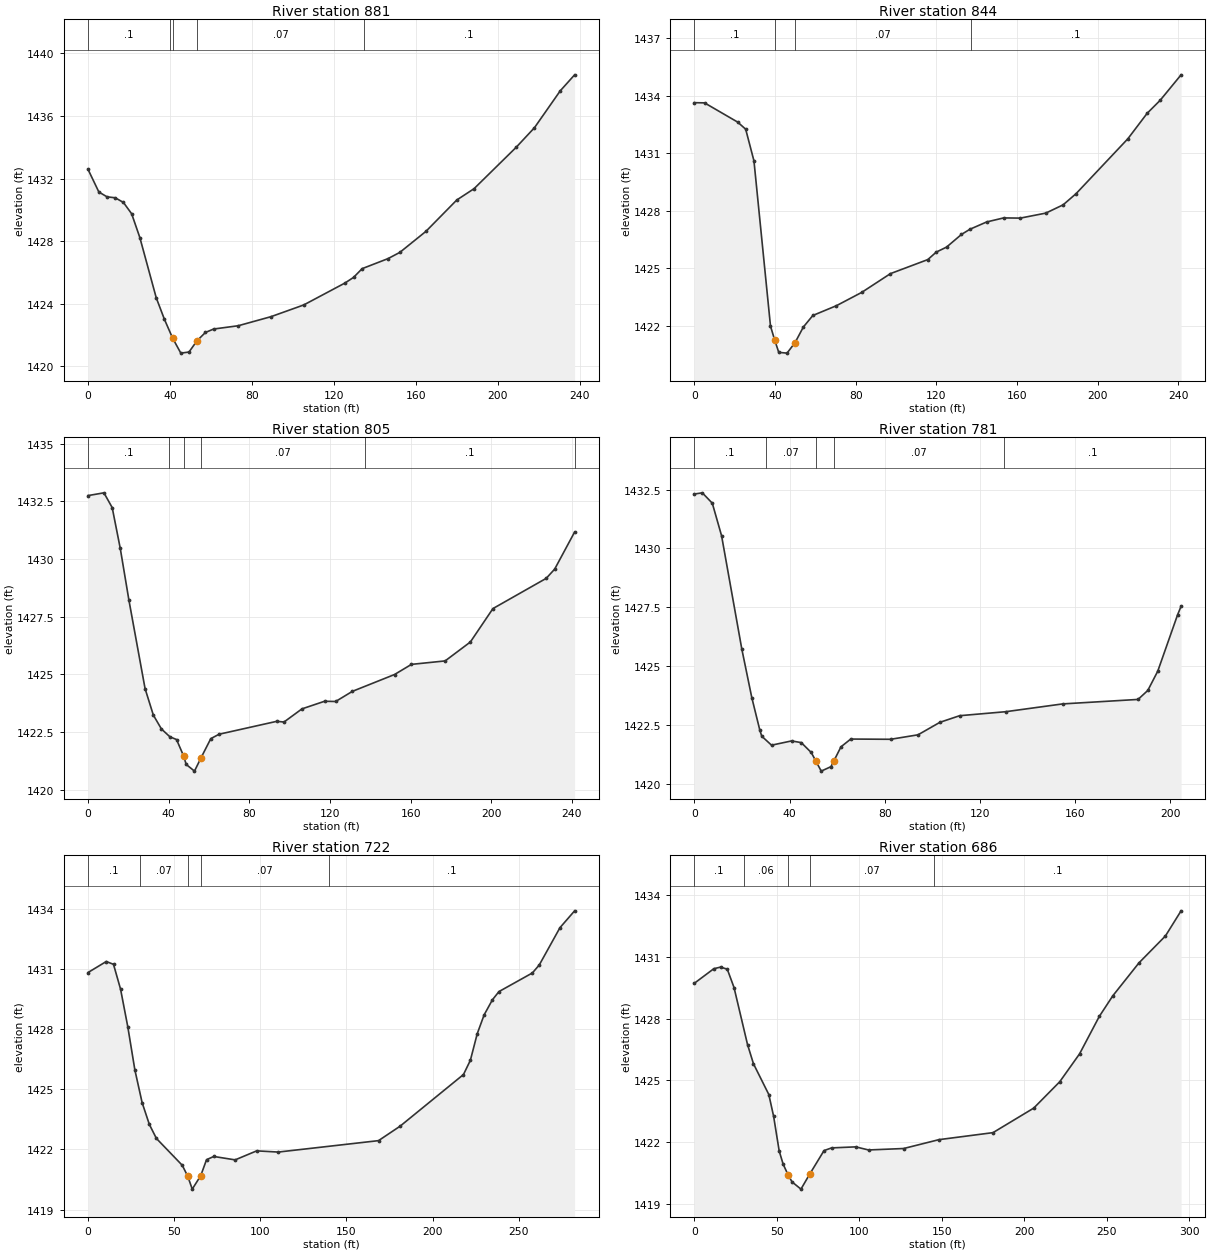
Type RM Length L Ch R = 1 ,881     ,38.7,37.1,34.9
XS GIS Cut Line= 3
2197446.91011787752138.8546661112197571.43572821 752135.19214816
2197678.86958811752100.398227625
#Sta/Elev= 30
       0 1432.59     5.3 1431.14     9.3 1430.83    13.3 1430.77    17.3 1430.47
    21.3 1429.75    25.3 1428.23    33.3 1424.38    37.3    1423    41.3  1421.8
    45.3 1420.84    49.3 1420.91    53.2 1421.63    57.3 1422.16    61.3 1422.38
    73.3 1422.59    89.3 1423.17   105.3 1423.92   125.4 1425.32   129.6 1425.68
   133.8 1426.24   146.4 1426.88   152.2 1427.28   164.9 1428.62     180 1430.63
   188.4 1431.35     209    1434   217.9 1435.25   230.5 1437.61   237.5 1438.63
#Mann= 5 ,-1,0
       0      .1       0      40     .07       0    41.3    .045       0
    53.2     .07       0  134.58      .1       0
Bank Sta=41.3,53.2
XS Rating Curve= 0 ,0
Exp/Cntr(USF)=0,0
Exp/Cntr=0.3,0.1

Type RM Length L Ch R = 1 ,844     ,39.2,39.3,39.3
XS GIS Cut Line= 3
2197443.24759992752181.5840422072197538.47306665752162.050613135
2197676.42790947752120.542076356
#Sta/Elev= 30
       0 1433.63       5 1433.62    21.4 1432.62    25.4 1432.25    29.5  1430.6
    37.7    1422    39.71421.297    41.8 1420.63    45.9 1420.59    49.9 1421.14
      54 1421.95    58.7 1422.55    70.4 1423.06    82.9 1423.75    97.2 1424.73
   115.7 1425.46   119.9 1425.85     125 1426.11   132.4 1426.77   136.6 1427.04
   144.9 1427.42   153.3 1427.63   161.6 1427.62   174.2 1427.88   182.8 1428.31
   189.2 1428.89   214.9 1431.75   224.5 1433.08   230.9 1433.75   241.3 1435.08
#Mann= 4 ,-1,0
       0      .1       0    39.7    .045       0    49.9     .07       0
  137.21      .1       0
Bank Sta=39.7,49.9
XS Rating Curve= 0 ,0
Exp/Cntr(USF)=0,0
Exp/Cntr=0.3,0.1

Type RM Length L Ch R = 1 ,805     ,25.4,24.3,23.5
XS GIS Cut Line= 3
2197444.46843924752221.2613200112197539.69390596752201.727890938
2197677.64874879752160.219354159
#Sta/Elev= 30
       0 1432.75     7.9 1432.87      12 1432.23      16 1430.46    20.3 1428.21
    28.3 1424.38    32.4 1423.23    36.4 1422.63    40.6 1422.29    43.9 1422.17
    47.41421.461    48.7 1421.09    52.8  1420.8      56 1421.37    60.9 1422.21
      65  1422.4    93.6 1422.96    97.2 1422.93   106.1  1423.5   117.3 1423.83
   122.8 1423.82   131.1 1424.26     152 1424.99   160.4 1425.43   177.1 1425.58
   189.6  1426.4   200.8 1427.85   227.2 1429.16   231.4 1429.56   241.3 1431.17
#Mann= 6 ,-1,0
       0      .1       0      40     .07       0    47.4    .045       0
      56     .07       0  137.21      .1       0  241.27     .07       0
Bank Sta=47.4,56
XS Rating Curve= 0 ,0
Exp/Cntr(USF)=0,0
Exp/Cntr=0.3,0.1

Type RM Length L Ch R = 1 ,781     ,56,58.5,57.3
XS GIS Cut Line= 2
2197453.01431446752248.119784985 2197649.5694445752191.350756743
#Sta/Elev= 29
       0 1432.31     3.3 1432.36     7.5 1431.92    11.4 1430.54    19.9 1425.74
    24.1 1423.68    27.5 1422.29    28.3 1422.04    32.4 1421.66    40.8 1421.84
    44.9 1421.77    49.1 1421.35   51.02 1420.99    53.3 1420.56    57.4 1420.75
    58.6 1420.99    61.6 1421.59    65.7 1421.92    82.5 1421.91      94  1422.1
   103.2 1422.63   111.5 1422.91   130.9 1423.08   154.8 1423.41   186.5  1423.6
   190.6 1423.98   194.8  1424.8   203.1 1427.18   204.6 1427.55
#Mann= 5 ,-1,0
       0      .1       0      30     .07       0   51.02    .045       0
    58.6     .07       0     130      .1       0
Bank Sta=51.02,58.6
XS Rating Curve= 0 ,0
Exp/Cntr(USF)=0,0
Exp/Cntr=0.3,0.1

Type RM Length L Ch R = 1 ,722     ,38.8,36.2,29.3
XS GIS Cut Line= 3
2197449.96221616752302.4471345932197644.07566757752247.509365327
2197724.65106249752243.846847376
#Sta/Elev= 30
       0 1430.83    10.6 1431.38    14.8 1431.24    18.9    1430    23.1 1428.12
    27.2 1425.97    31.4 1424.34    35.6 1423.25    39.7 1422.55    54.7 1421.21
    57.9 1420.66    60.5 1420.02   65.41 1420.69    68.8 1421.49      73 1421.65
    85.4 1421.48    97.9 1421.93   110.4 1421.87   168.6 1422.44   181.1 1423.16
   217.9 1425.74   221.9 1426.45   225.9 1427.78   229.9 1428.72   234.7 1429.47
   238.5 1429.88   257.9 1430.81   261.9 1431.21   273.9 1433.07   282.4 1433.91
#Mann= 5 ,-1,0
       0      .1       0      30     .07       0    57.9    .045       0
   65.41     .07       0     140      .1       0
Bank Sta=57.9,65.41
XS Rating Curve= 0 ,0
Exp/Cntr(USF)=0,0
Exp/Cntr=0.3,0.1

Type RM Length L Ch R = 1 ,686     ,37.7,39.1,43.3
XS GIS Cut Line= 6
2197448.81469047752341.849579341 2197481.3778486752334.406571769
2197534.40927755752302.773789588 2197589.3014584752282.305518764
2197640.41314962752272.5365713262197729.67025465752266.282677251
#Sta/Elev= 30
       0 1429.72    11.7 1430.42    15.8  1430.5    19.9  1430.4      24 1429.51
    32.2 1426.74    35.8 1425.81    45.1 1424.32      48 1423.27    51.4 1421.58
    53.8 1420.94    56.8 1420.42    59.2 1420.08    64.6 1419.73    69.81420.443
    78.6  1421.6    83.2 1421.73    97.8 1421.78   105.6 1421.63   126.9  1421.7
   148.3 1422.13   181.1 1422.47   205.8 1423.66   221.6 1424.94   233.6 1426.29
   245.6 1428.11   253.8 1429.11   269.7 1430.71   285.7 1432.01   295.2 1433.23
#Mann= 5 ,-1,0
       0      .1       0      30     .06       0    56.8    .045       0
    69.8     .07       0  145.15      .1       0
Bank Sta=56.8,69.8
XS Rating Curve= 0 ,0
Exp/Cntr(USF)=0,0
Exp/Cntr=0.3,0.1

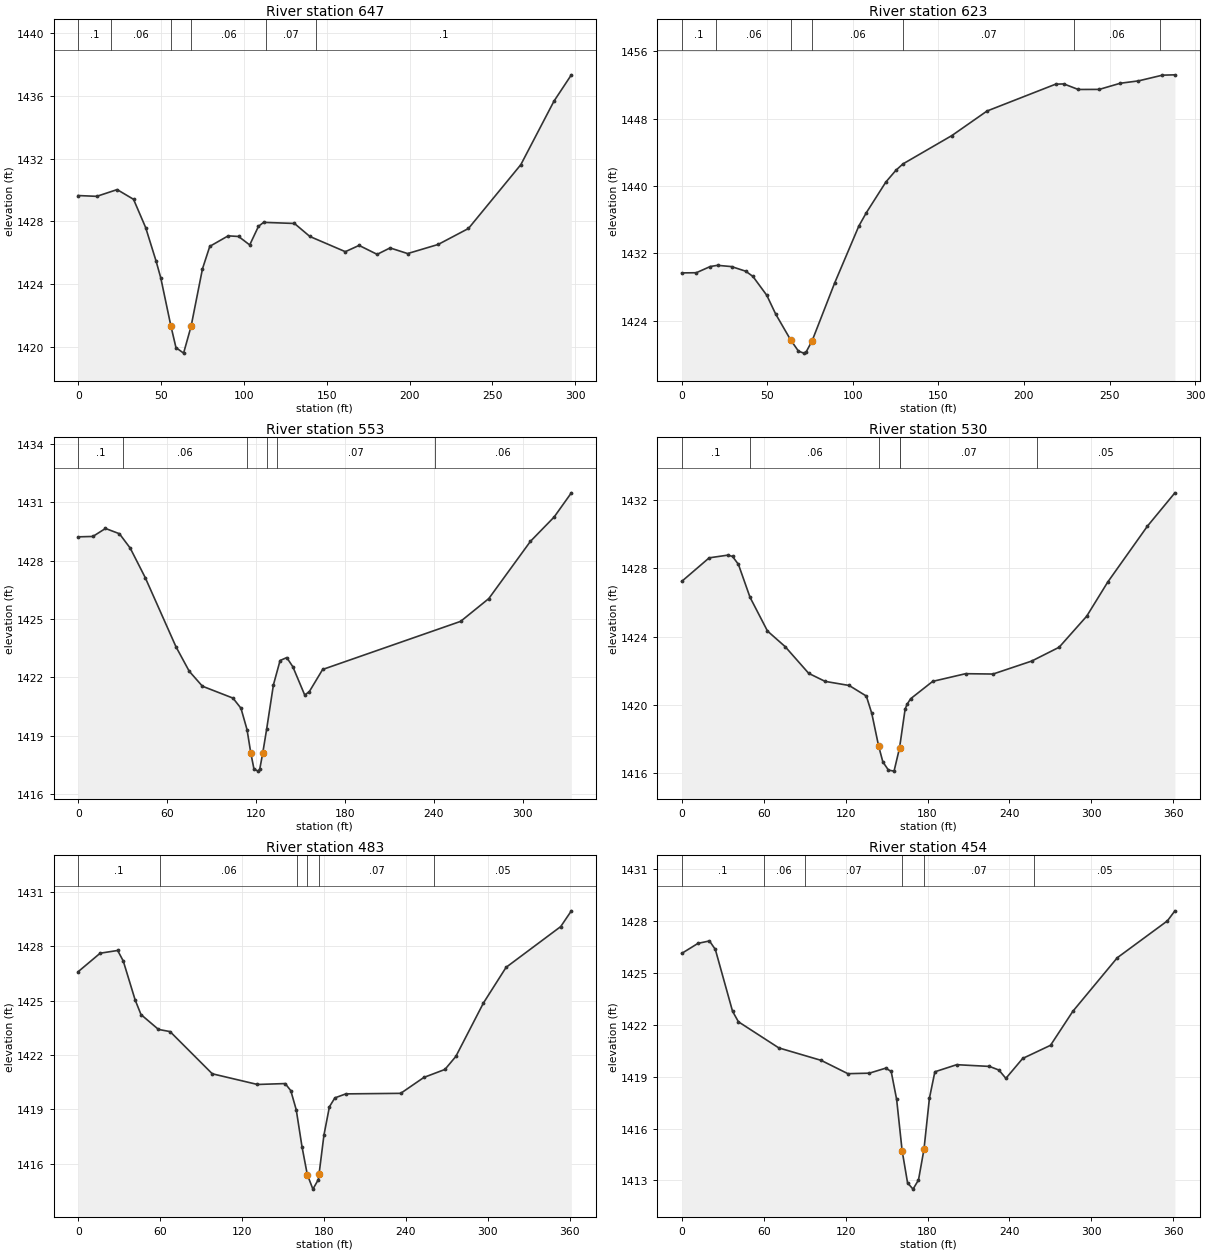
Type RM Length L Ch R = 1 ,647     ,23.4,23.8,24.4
XS GIS Cut Line= 6
2197461.22953406752376.7681702532197493.79269219752369.325162681
2197532.97928972752347.6181893232197546.21370149752326.094406988
2197601.71630199752305.0157165062197734.76006234752288.382455334
#Sta/Elev= 30
       0 1429.65    11.2  1429.6    23.5 1430.03    33.4 1429.41    40.7 1427.61
      47 1425.47    49.8 1424.41    55.9 1421.35      59 1419.95    63.6  1419.6
    68.1  1421.3      75 1424.98    79.4 1426.41    90.5 1427.08    96.8 1427.04
   103.5  1426.5   108.8 1427.69   111.9 1427.94   130.5 1427.87   139.8 1427.04
   161.2 1426.07   169.5 1426.47   180.4  1425.9   188.2 1426.31   198.8 1425.95
   217.2 1426.53   235.5 1427.55   267.1 1431.62   287.1 1435.67   297.6 1437.35
#Mann= 6 ,-1,0
       0      .1       0      20     .06       0    55.9    .045       0
    68.1     .06       0  113.47     .07       0  143.47      .1       0
Bank Sta=55.9,68.1
XS Rating Curve= 0 ,0
Exp/Cntr(USF)=0,0
Exp/Cntr=0.3,0.1

Type RM Length L Ch R = 1 ,623     ,71.1,70.5,69.9
XS GIS Cut Line= 4
2197464.00186831752378.7495919072197503.06872645752389.126726102
 2197574.4878265752355.553644883 2197739.3011343752318.928465373
#Sta/Elev= 30
       0 1429.66     8.5 1429.68    16.7 1430.42    20.9 1430.56    29.1 1430.41
    37.4 1429.86    41.6 1429.24    49.7    1427    54.9 1424.77    63.7 1421.68
    68.2 1420.37    71.3 1420.13    72.6 1420.23    76.2  1421.6    89.3 1428.43
   103.5 1435.23   107.9 1436.82   119.3 1440.46   125.2 1441.86   129.3 1442.61
   157.9 1445.98   178.4 1448.89   218.5 1452.08   223.3 1452.11   231.7 1451.45
     244 1451.46   256.3 1452.19   266.9 1452.47   280.9 1453.15   288.2 1453.19
#Mann= 7 ,-1,0
       0      .1       0      20     .06       0    63.7    .045       0
    76.2     .06       0  129.34     .07       0  229.34     .06       0
  279.34      .1       0
Bank Sta=63.7,76.2
XS Rating Curve= 0 ,0
Exp/Cntr(USF)=0,0
Exp/Cntr=0.3,0.1

Type RM Length L Ch R = 1 ,553     ,14.3,22.1,31.3
XS GIS Cut Line= 4
2197459.36878217752397.2364410772197552.40637682 752444.68561435
2197584.03915901752427.0084713662197775.69660399752415.843960007
#Sta/Elev= 30
       0 1429.22     9.9 1429.24    18.4 1429.65    27.8 1429.38    35.1 1428.64
    45.2 1427.13      66 1423.57    74.9 1422.32    83.8 1421.55   104.4 1420.94
   109.8 1420.42   113.9 1419.32  116.46 1418.11   118.6 1417.29   121.5 1417.19
   122.5  1417.3   124.5 1418.12   127.1 1419.33   131.7 1421.62   136.2 1422.87
   140.7 1423.02   144.8 1422.55   152.8  1421.1   155.9 1421.27   164.9 1422.41
     258 1424.88     277 1426.05   305.1 1428.99   321.1 1430.24   332.7 1431.48
#Mann= 6 ,-1,0
       0      .1       0      30     .06       0   113.9    .045       0
   127.1     .06       0  134.44     .07       0  240.68     .06       0
Bank Sta=116.46,124.5
XS Rating Curve= 0 ,0
Exp/Cntr(USF)=0,0
Exp/Cntr=0.3,0.1

Type RM Length L Ch R = 1 ,530     ,47.9,47.4,45.5
XS GIS Cut Line= 5
2197433.31825567752408.4009524352197555.19750466752453.989373815
2197604.50742983752462.3627573332197644.51359553752465.153885173
2197784.06998751752445.615990296
#Sta/Elev= 30
       0 1427.24    20.1 1428.62    33.9 1428.78    37.2  1428.7    41.5 1428.24
      50 1426.31    62.8 1424.33    75.7 1423.42      93 1421.85     105 1421.38
   122.6 1421.14   135.2 1420.52   139.2  1419.5   144.2 1417.59   147.3 1416.66
   151.4 1416.18   155.5 1416.12   159.5 1417.47   163.6 1419.75     165 1420.03
   167.6 1420.36   183.8 1421.38   207.9 1421.83     228 1421.81   256.3 1422.57
   276.4 1423.38   296.6  1425.2     312  1427.2   341.1 1430.48   361.2 1432.43
#Mann= 6 ,-1,0
       0      .1       0      50     .06       0   144.2    .045       0
   159.5     .06       0  160.13     .07       0  260.25     .05       0
Bank Sta=144.2,159.5
XS Rating Curve= 0 ,0
Exp/Cntr(USF)=0,0
Exp/Cntr=0.3,0.1

Type RM Length L Ch R = 1 ,483     ,30.2,28.6,27.1
XS GIS Cut Line= 5
2197429.13156391752449.802682055 2197551.0108129752495.391103435
2197600.32073807752503.7644869542197640.32690377752506.555614793
2197779.88329575752487.017719916
#Sta/Elev= 30
       0  1426.6    16.1 1427.62    28.9 1427.77      33 1427.19    41.7 1425.04
      46 1424.23    58.8 1423.41    67.3 1423.29    98.2 1420.96   131.3 1420.37
   151.6 1420.42   155.7 1420.03   159.7 1418.97   163.9 1416.94   167.8 1415.39
   171.9 1414.59   175.9 1415.12  176.45 1415.45     180 1417.58     184 1419.14
     188 1419.63     196 1419.85   236.2 1419.88   253.2 1420.76   268.6  1421.2
   276.6 1421.92   296.8 1424.87   313.4 1426.84   353.4 1429.09   361.2 1429.96
#Mann= 6 ,-1,0
       0      .1       0      60     .06       0  160.13     .07       0
   167.8    .045       0  176.45     .07       0  260.25     .05       0
Bank Sta=167.8,176.45
XS Rating Curve= 0 ,0
Exp/Cntr(USF)=0,0
Exp/Cntr=0.3,0.1

Type RM Length L Ch R = 1 ,454     ,86,85.4,84.3
XS GIS Cut Line= 4
2197424.94487215752492.1347876222197533.79885789752529.349825483
2197656.60848283752532.1409533232197777.55735588752507.951178713
#Sta/Elev= 30
       0 1426.12    11.9  1426.7    20.3 1426.84    24.6 1426.35    37.2 1422.78
    41.5 1422.17    71.1 1420.66   102.1 1419.94   121.7 1419.17   137.4  1419.2
   149.4 1419.49   153.4  1419.3   157.4 1417.68   161.4 1414.73   165.4 1412.86
   169.4  1412.5   173.4 1413.03   177.4 1414.79   181.4 1417.75   185.4 1419.28
   201.4 1419.69   225.4 1419.59   232.3 1419.38   237.4  1418.9   249.7 1420.05
   270.1 1420.81   286.4 1422.77     319 1425.87   355.7    1428   361.2 1428.58
#Mann= 6 ,-1,0
       0      .1       0      60     .06       0      90     .07       0
   161.4    .045       0   177.4     .07       0  257.88     .05       0
Bank Sta=161.4,177.4
XS Rating Curve= 0 ,0
Exp/Cntr(USF)=0,0
Exp/Cntr=0.3,0.1

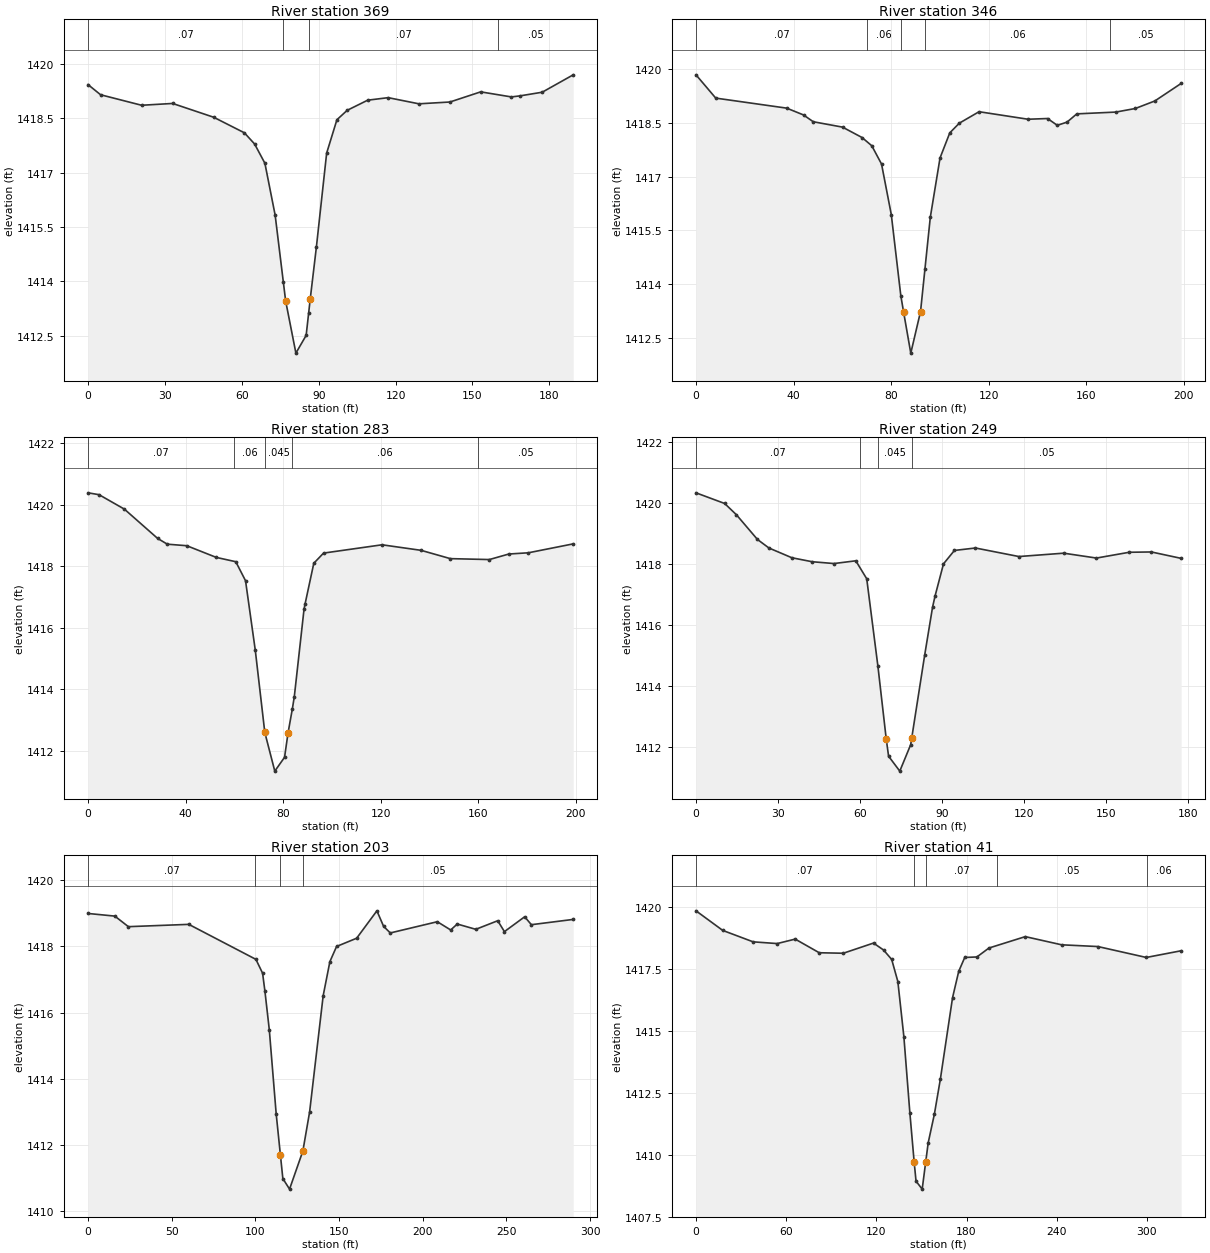
Type RM Length L Ch R = 1 ,369     ,22.7,23,23.2
XS GIS Cut Line= 2
2197515.26536527752620.1012348092197704.25129154752608.564303263
#Sta/Elev= 28
       0 1419.43     4.9 1419.15    20.9 1418.86      33 1418.91      49 1418.53
      61  1418.1      65 1417.79      69 1417.26      73 1415.83    76.2 1413.98
    77.1 1413.46    81.1 1412.02    85.1 1412.51    86.11413.141    86.7 1413.52
    89.1 1414.95    93.1 1417.54    97.1 1418.46   101.1 1418.72   109.1    1419
   117.1 1419.07   129.1  1418.9   141.2 1418.95   153.2 1419.23   165.2 1419.09
   168.6 1419.12   177.2 1419.22   189.3  1419.7
#Mann= 4 ,-1,0
       0     .07       0    76.2    .045       0    86.1     .07       0
     160     .05       0
Bank Sta=77.1,86.7
XS Rating Curve= 0 ,0
Exp/Cntr(USF)=0,0
Exp/Cntr=0.3,0.1

Type RM Length L Ch R = 1 ,346     ,63.1,63,63
XS GIS Cut Line= 2
2197508.12345526752641.526964823   2197706.99818752633.835677125
#Sta/Elev= 29
       0 1419.84     8.1 1419.19    37.2 1418.91    44.1 1418.72    48.1 1418.53
    60.1 1418.38    68.1 1418.09    72.1 1417.86    76.1 1417.35    80.1 1415.94
      841413.678   85.12 1413.23    88.1 1412.07    92.1 1413.23    93.91414.413
    96.1 1415.86   100.1 1417.52   104.1 1418.22     108 1418.49   116.1 1418.81
   136.2  1418.6   144.2 1418.62   148.2 1418.43   152.2 1418.52   156.2 1418.75
   172.2  1418.8   180.2  1418.9   188.2 1419.11     199  1419.6
#Mann= 5 ,-1,0
       0     .07       0      70     .06       0      84    .045       0
    93.9     .06       0     170     .05       0
Bank Sta=85.12,92.1
XS Rating Curve= 0 ,0
Exp/Cntr(USF)=0,0
Exp/Cntr=0.3,0.1

Type RM Length L Ch R = 1 ,283     ,33.8,33.7,33.6
XS GIS Cut Line= 2
2197519.66038681752704.1560217862197718.53511155752696.464734089
#Sta/Elev= 27
       0 1420.39     4.5 1420.33    14.9 1419.86    28.5 1418.91    32.5 1418.72
    40.5 1418.67    52.6 1418.29    60.6 1418.15    64.6 1417.53    68.6 1415.27
    72.51412.598    76.6 1411.34    80.6 1411.79   82.03 1412.58    83.81413.364
    84.6 1413.76    88.6 1416.61      89 1416.77    92.6  1418.1    96.6 1418.43
   120.6  1418.7   136.6 1418.52   148.6 1418.25   164.6 1418.22   172.6  1418.4
   180.6 1418.44     199 1418.73
#Mann= 5 ,-1,0
       0     .07       0      60     .06       0    72.5    .045       0
    83.8     .06       0     160     .05       0
Bank Sta=72.5,82.03
XS Rating Curve= 0 ,0
Exp/Cntr(USF)=0,0
Exp/Cntr=0.3,0.1

Type RM Length L Ch R = 1 ,249     ,46.9,46.5,46.1
XS GIS Cut Line= 2
2197525.70354143752738.2174387312197703.15253616752729.976773341
#Sta/Elev= 28
       0 1420.34    10.5 1419.99    14.8 1419.62    22.5 1418.81    26.7 1418.53
    35.1 1418.21    42.5 1418.08    50.5 1418.02    58.5 1418.11    62.5 1417.52
    66.61414.645   69.63 1412.27    70.5  1411.7    74.6 1411.21    78.6 1412.08
      791412.311    83.7 1415.01    86.6 1416.59    87.5 1416.95    90.6 1418.01
    94.6 1418.45   102.3 1418.53   118.2 1418.25   134.6 1418.36   146.6  1418.2
   158.6 1418.39   166.7  1418.4   177.6 1418.19
#Mann= 4 ,-1,0
       0     .07       0      60     .05       0    66.6    .045       0
      79     .05       0
Bank Sta=69.63,79
XS Rating Curve= 0 ,0
Exp/Cntr(USF)=0,0
Exp/Cntr=0.3,0.1

Type RM Length L Ch R = 1 ,203     ,161,161.7,161
XS GIS Cut Line= 2
2197480.20211413752791.368401942 2197769.1086677752767.289096365
#Sta/Elev= 30
       0    1419      16 1418.92    24.1  1418.6    60.2 1418.67   100.3 1417.61
   104.3 1417.19   105.7 1416.64   108.3 1415.48   112.4 1412.94114.96761411.671
   116.4 1410.97   120.4 1410.65128.36751411.805   132.4 1412.99   140.5 1416.51
   144.5 1417.54   148.5    1418   160.5 1418.25   172.6 1419.08   176.6 1418.61
   180.6 1418.41   208.7 1418.75   216.7  1418.5   220.6 1418.68   231.7 1418.52
   244.8 1418.78   248.8 1418.45   260.9  1418.9   264.9 1418.66   289.9 1418.82
#Mann= 4 ,-1,0
       0     .07       0     100     .05       0114.9676    .045       0
128.3675     .05       0
Bank Sta=114.9676,128.3675
XS Rating Curve= 0 ,0
Exp/Cntr(USF)=0,0
Exp/Cntr=0.3,0.1

Type RM Length L Ch R = 1 ,41      ,,,
XS GIS Cut Line= 4
2197478.19731154752949.6266257882197594.08544124752945.203414731
 2197667.5107448752933.7030659822197799.25698885  752919.7782358
#Sta/Elev= 30
       0 1419.84    17.8 1419.05      38 1418.59      54 1418.52      66  1418.7
      82 1418.15      98 1418.13   118.1 1418.54   124.8 1418.26   130.2 1417.88
   134.3 1416.99   138.3 1414.77   142.3 1411.69  145.13 1409.73   146.4 1408.94
   150.5 1408.62   152.8  1409.7   154.5 1410.49   158.6 1411.64   162.6 1413.06
   170.7 1416.34   174.8  1417.4   178.8 1417.96   186.9 1417.98   194.9 1418.34
   219.1  1418.8   243.3 1418.47   267.4  1418.4   299.6 1417.96   322.8 1418.23
#Mann= 5 ,-1,0
       0     .07       0  145.13    .045       0   152.8     .07       0
  200.29     .05       0  300.29     .06       0
Bank Sta=145.13,152.8
XS Rating Curve= 0 ,0
Exp/Cntr(USF)=0,0
Exp/Cntr=0.3,0.1
LCMann Table=0

Chan Stop Cuts=-1
Use User Specified Reach Order=0
Composite Channel Slope=5